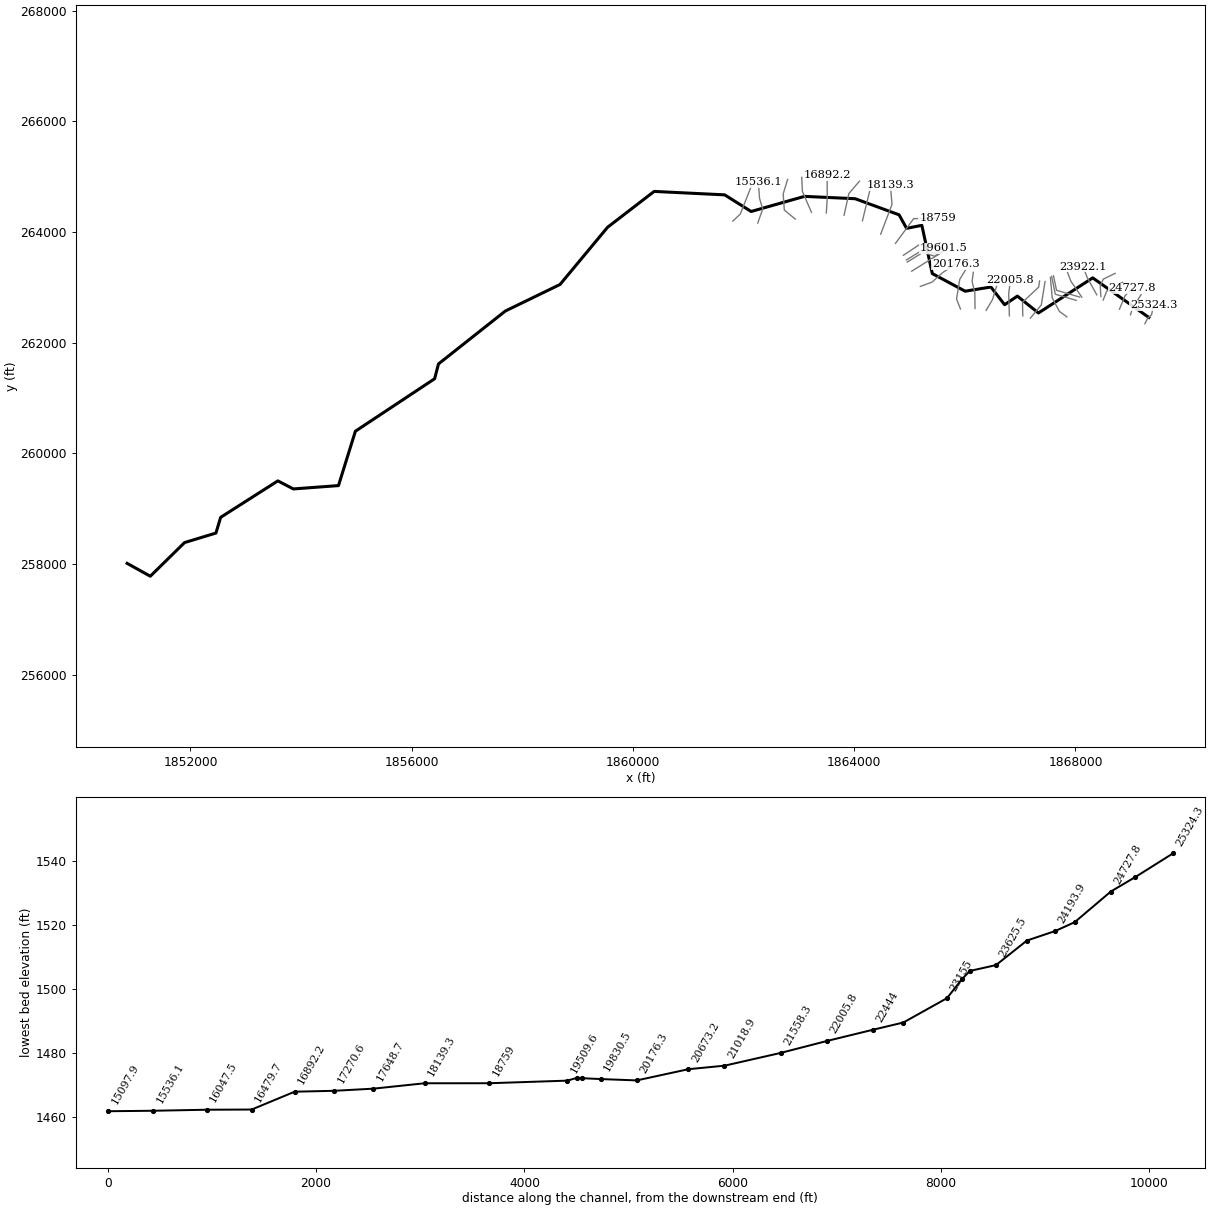
--- RACCOONRN.prj (project) ---

Proj Title=RACCOONRN
Current Plan=p01
Default Exp/Contr=0,0
English Units
Geom File=g01
Flow File=f01
Plan File=p01
BEGIN DESCRIPTION:
END DESCRIPTION:
DSS Export Rating Curves= 0
DSS Export Rating Curve Sorted= 0
DSS Export Volume Flow Curves= 0
DXF OffsetX= 0
DXF OffsetY= 0
DXF ScaleX= 0
DXF ScaleY= 0

--- RACCOONRN.p01 (plan) ---

Plan Title=Floodplain
Program Version=4.00
Geom File=g01
Flow File=f01
K Sum by GR=0
Std Step Tol=0.01
Critical Tol=0.01
Num of Std Step Trials=20
Max Error Tol=0.3
Flow Tol Ratio=0.001
Split Flow NTrial=30
Split Flow Tol=0.02
Split Flow Ratio=0.02
Log Output Level=0
Friction Slope Method=1
Unsteady Friction Slope Method=2
Unsteady Bridges Friction Slope Method=1
Global Log Level=0
CheckData=False
Run HTab=0
Run UNet=0
Run PostProcess=0
UNET Theta=0
UNET Theta Warmup=0
UNET ZTol=0
UNET ZSATol=0
UNET MxIter=0
UNET MaxInSteps=0
UNET DtIC=0
UNET DtMin=0
UNET MaxCRTS=0
UNET WFStab=0
UNET SFStab=0
UNET WFX=0
UNET SFX=0
UNET DSS MLevel=0
UNET DZMax Abort=0
UNET Convert EG Bridges=0
UNET Use Existing IB Tables=0
UNET Froude Limit=0
UNET Froude Power=0
Write IC File=0
Echo Input=False
Echo Output=False
Write Detailed=0

--- RACCOONRN.f01 (steady flow) ---

Flow Title=NFF Regression Equation
Program Version=4.00
Number of Profiles=1
Profile Names=P100yr
River Rch & RM=RACCOONRN,Main      ,25324.3
504.8877
River Rch & RM=RACCOONRN,Main      ,24193.9
544.8472
River Rch & RM=RACCOONRN,Main      ,23922.1
599.7842
River Rch & RM=RACCOONRN,Main      ,22736.2
610.7018
River Rch & RM=RACCOONRN,Main      ,22444
685.5041
River Rch & RM=RACCOONRN,Main      ,21018.9
695.3946
River Rch & RM=RACCOONRN,Main      ,19830.5
769.1409
River Rch & RM=RACCOONRN,Main      ,18139.3
827.6316
River Rch & RM=RACCOONRN,Main      ,15536.1
1039.945
River Rch & RM=RACCOONRN,Main      ,15536.1
868.8471
River Rch & RM=RACCOONRN,Main      ,13468.3
1142.934
River Rch & RM=RACCOONRN,Main      ,8261.5
1242.802
River Rch & RM=RACCOONRN,Main      ,4858.4
1371.016
River Rch & RM=RACCOONRN,Main      ,1496
1481.830
River Rch & RM=RACCOONRN,Main      ,132.3
1542.947
Boundary for River Rch & Prof#=RACCOONRN,Main      ,1
Up Type=0
Dn Type=3
Dn Slope=0.010247

--- RACCOONRN.g01 (geometry) ---

Geom Title=USGS 10m DEM
Program Version=5.03

River Reach=RACCOONRN       ,Main
Reach XY= 30
     1869326.733      262454.819     1868311.824      263169.985
     1867330.936      262535.517     1866949.919       262840.25
     1866719.091      262684.582     1866471.286      263004.802
     1866006.006      262928.949     1865411.845      263247.209
     1865223.088      264119.166     1864946.748      264064.663
     1864811.485      264308.929     1864017.471      264599.989
     1863101.198      264642.317     1862137.082      264369.153
      1861658.12      264669.692     1860383.538      264731.843
     1859541.228      264083.825     1858681.142      263049.904
     1857692.694      262570.347     1856484.567      261614.934
     1856414.537      261346.973     1854982.303       260399.01
     1854676.513      259416.551     1853860.904       259356.23
     1853580.528      259501.627     1852546.346      258843.028
     1852461.055      258559.108     1851893.805      258386.979
     1851274.475      257778.997     1850855.459      258011.831

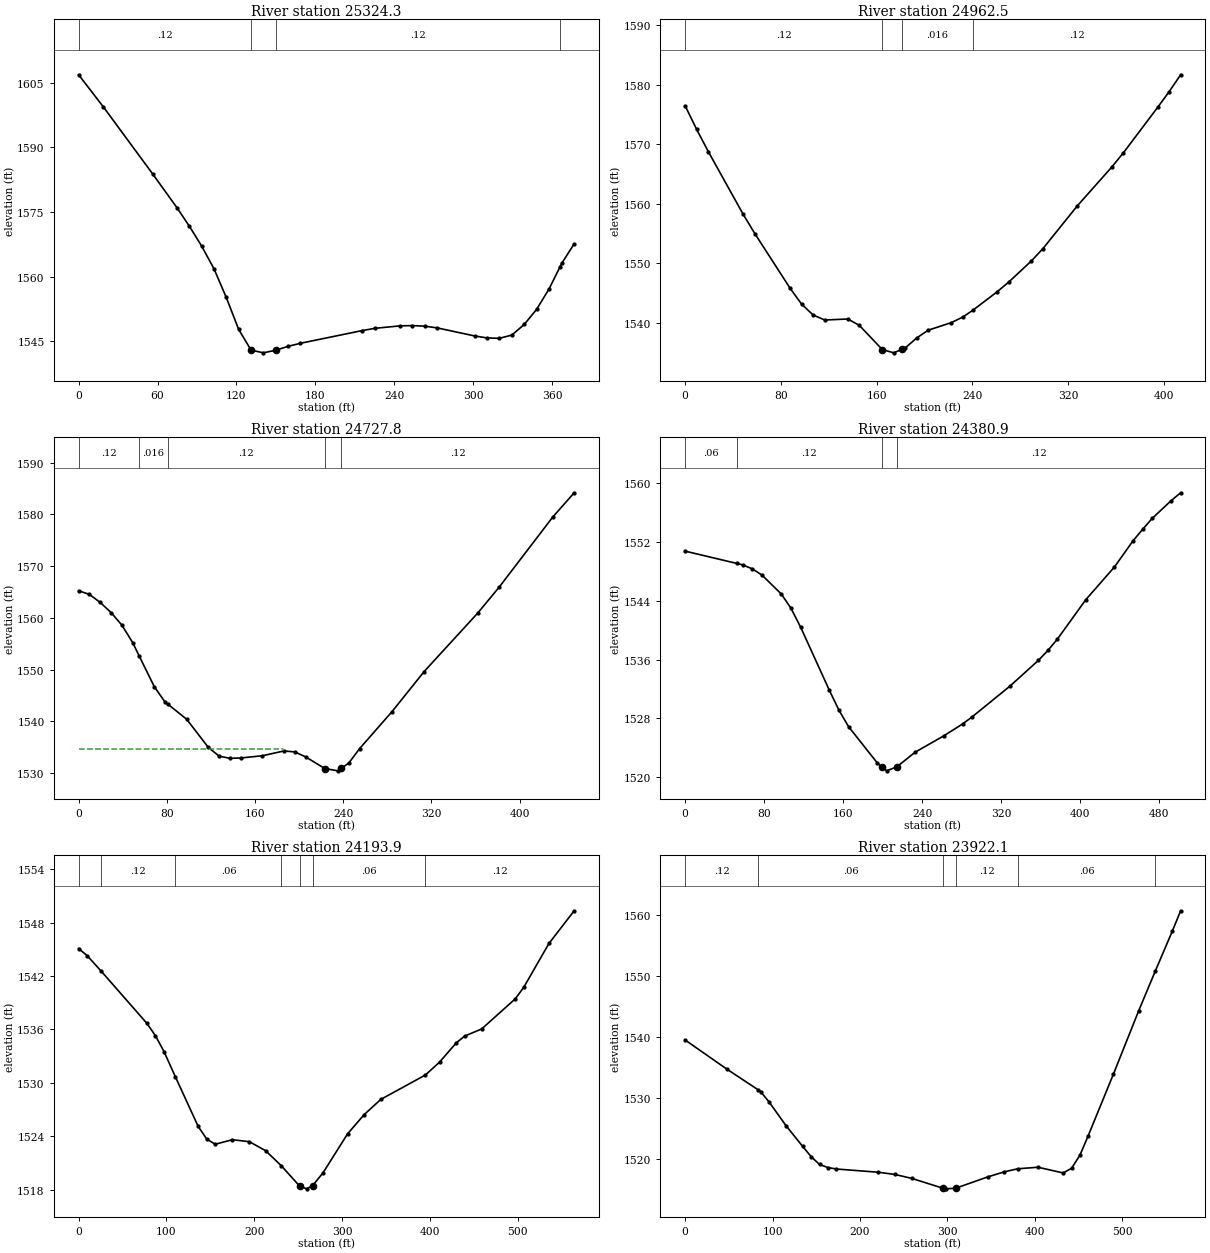
Type RM Length L Ch R = 1 ,25324.3 ,355.5,361.8,368
XS GIS Cut Line= 4
     1869254.893      262341.384     1869306.069      262441.354
     1869375.987      262504.145     1869412.446      262670.811
#Sta/Elev= 30
       0 1606.89    18.7 1599.47    56.2  1583.9    74.9 1575.96    84.2 1571.72
    93.6 1567.08     103 1561.79   112.3 1555.15   121.7 1547.75   131.1 1542.94
   140.5 1542.29   149.9  1542.9   159.3  1543.8   168.7 1544.51   215.8 1547.47
   225.2 1547.98   244.2 1548.55   253.7 1548.62   263.2 1548.49   272.6 1548.09
   301.1 1546.22   310.5 1545.76     320 1545.66   329.5 1546.42     339 1548.91
   348.4 1552.42   357.9 1557.19  366.111562.263   367.4 1563.06   376.9 1567.62
#Mann= 4 ,-1 , 0
       0     .12       0   131.1    .045       0   149.9     .12       0
  366.11    .016       0
Bank Sta=131.1,149.9
XS Rating Curve= 0 ,0
Exp/Cntr=0.3,0.1

Type RM Length L Ch R = 1 ,24962.5 ,230.9,234.8,238.6
XS GIS Cut Line= 3
     1868994.477      262502.843     1869030.935      262623.936
     1869185.883      262866.124
#Sta/Elev= 30
       0 1576.47     9.7 1572.47    19.5 1568.71    48.6 1558.18    58.4 1554.92
    87.6 1545.81    97.3  1543.1     107 1541.27   116.7 1540.43     136  1540.6
   145.6 1539.52   164.8 1535.46   174.4 1534.91     181 1535.49     184 1535.75
   193.6 1537.43   203.1 1538.72   222.3 1539.98   231.9 1540.92  240.461542.079
   260.6 1545.16   270.2 1546.78   289.4 1550.38     299 1552.45   327.7 1559.63
   356.5 1566.16   366.1 1568.53   394.8 1576.19   404.4 1578.83     414 1581.67
#Mann= 4 ,-1 , 0
       0     .12       0   164.8    .045       0     181    .016       0
  240.46     .12       0
Bank Sta=164.8,181
XS Rating Curve= 0 ,0
Exp/Cntr=0.3,0.1

Type RM Length L Ch R = 1 ,24727.8 ,361.9,346.9,331.5
XS GIS Cut Line= 3
     1868795.258      262604.405     1868898.017      262848.383
     1869027.029      262980.707
#Sta/Elev= 30
       0 1565.24     9.8 1564.54    19.6 1562.98    29.4 1561.03    39.2  1558.6
      49 1555.22   54.77  1552.7    68.6  1546.7    78.4  1543.7   81.061543.274
      98 1540.38   117.7 1534.92   127.5 1533.24   137.3 1532.82   147.1 1532.89
   166.7 1533.32   186.3 1534.25   196.1 1534.06   205.9  1533.1   223.3 1530.85
   235.3  1530.4   238.3 1530.87   245.1 1531.92   254.9 1534.71   284.2 1541.84
   313.4 1549.61     362 1560.92   381.5 1565.95   430.1 1579.51   449.5  1584.2
#Mann= 5 ,-1 , 0
       0     .12       0   54.77    .016       0   81.06     .12       0
   223.3    .045       0   238.3     .12       0
#XS Ineff= 2 , 0
          185.76 1534.66
Permanent Ineff=
       F       F
Bank Sta=223.3,238.3
XS Rating Curve= 0 ,0
Exp/Cntr=0.3,0.1

Type RM Length L Ch R = 1 ,24380.9 ,172.6,187,201.2
XS GIS Cut Line= 3
     1868500.987      262768.468     1868566.091      262931.228
     1868851.248      263090.082
#Sta/Elev= 30
       0 1550.78   52.311549.107    58.4  1548.9    68.2 1548.36    77.9 1547.51
    97.4 1544.94   107.1 1543.02   116.9 1540.44   146.1 1531.81   155.8  1529.1
   165.6 1526.85   194.5 1521.94   199.31521.395   204.1 1520.85  214.491521.407
   232.9 1523.39   261.7  1525.6   280.9 1527.23   290.5 1528.19   328.9 1532.39
   357.7  1535.9   367.3 1537.25   376.9 1538.79   405.7 1544.17   434.5 1548.59
   453.7 1552.22   463.3 1553.76   472.9 1555.24   492.1 1557.66   501.7 1558.73
#Mann= 4 ,-1 , 0
       0     .06       0   52.31     .12       0   199.3    .045       0
  214.49     .12       0
Bank Sta=199.3,214.49
XS Rating Curve= 0 ,0
Exp/Cntr=0.3,0.1

Type RM Length L Ch R = 1 ,24193.9 ,249.5,271.8,292.8
XS GIS Cut Line= 4
     1868459.321      262833.572     1868447.602      263027.582
     1868502.289      263146.072     1868717.133      263251.541
#Sta/Elev= 30
       0 1545.09     9.7  1544.3   25.861542.535    77.8 1536.68    87.5 1535.29
    97.2 1533.52  110.251530.661     136 1525.13   145.8 1523.69   155.5  1523.1
   174.9 1523.61   194.4 1523.39     213 1522.37  230.861520.676   251.5 1518.41
   259.6 1518.09   266.5 1518.46   278.3  1519.9   306.2 1524.27   324.9 1526.41
     344 1528.14  394.861530.886     411 1532.34   430.2 1534.52   439.8 1535.27
   458.9 1536.06   497.2 1539.45   506.8 1540.74   535.5 1545.67   564.2 1549.34
#Mann= 7 ,-1 , 0
       0     .06       0   25.86     .12       0  110.25     .06       0
  230.86     .12       0   251.5    .045       0   266.5     .06       0
  394.86     .12       0
Bank Sta=251.5,266.5
XS Rating Curve= 0 ,0
Exp/Cntr=0.3,0.1

Type RM Length L Ch R = 1 ,23922.1 ,292.8,296.7,297.2
XS GIS Cut Line= 3
     1868385.102       262863.52     1868213.227      263174.718
     1868136.404      263371.332
#Sta/Elev= 30
       0 1539.51      48 1534.71   83.721531.328    86.5 1531.03    96.1 1529.34
   115.3 1525.49   134.5 1522.06   144.1  1520.4   153.7 1519.11   163.3 1518.61
     173 1518.37     221 1517.84   240.2 1517.47   259.4 1516.82   294.6 1515.23
   297.9 1515.12   309.6 1515.23   345.9 1517.07   365.1 1517.91  380.351518.405
   403.5 1518.66   432.3 1517.72   441.9 1518.49   451.5 1520.65     461 1523.85
   489.8 1533.94   518.6 1544.28  537.841550.873     557 1557.31   566.6 1560.68
#Mann= 6 ,-1 , 0
       0     .12       0   83.72     .06       0   294.6    .045       0
   309.6     .12       0  380.35     .06       0  537.84     .12       0
Bank Sta=294.6,309.6
XS Rating Curve= 0 ,0
Exp/Cntr=0.3,0.1

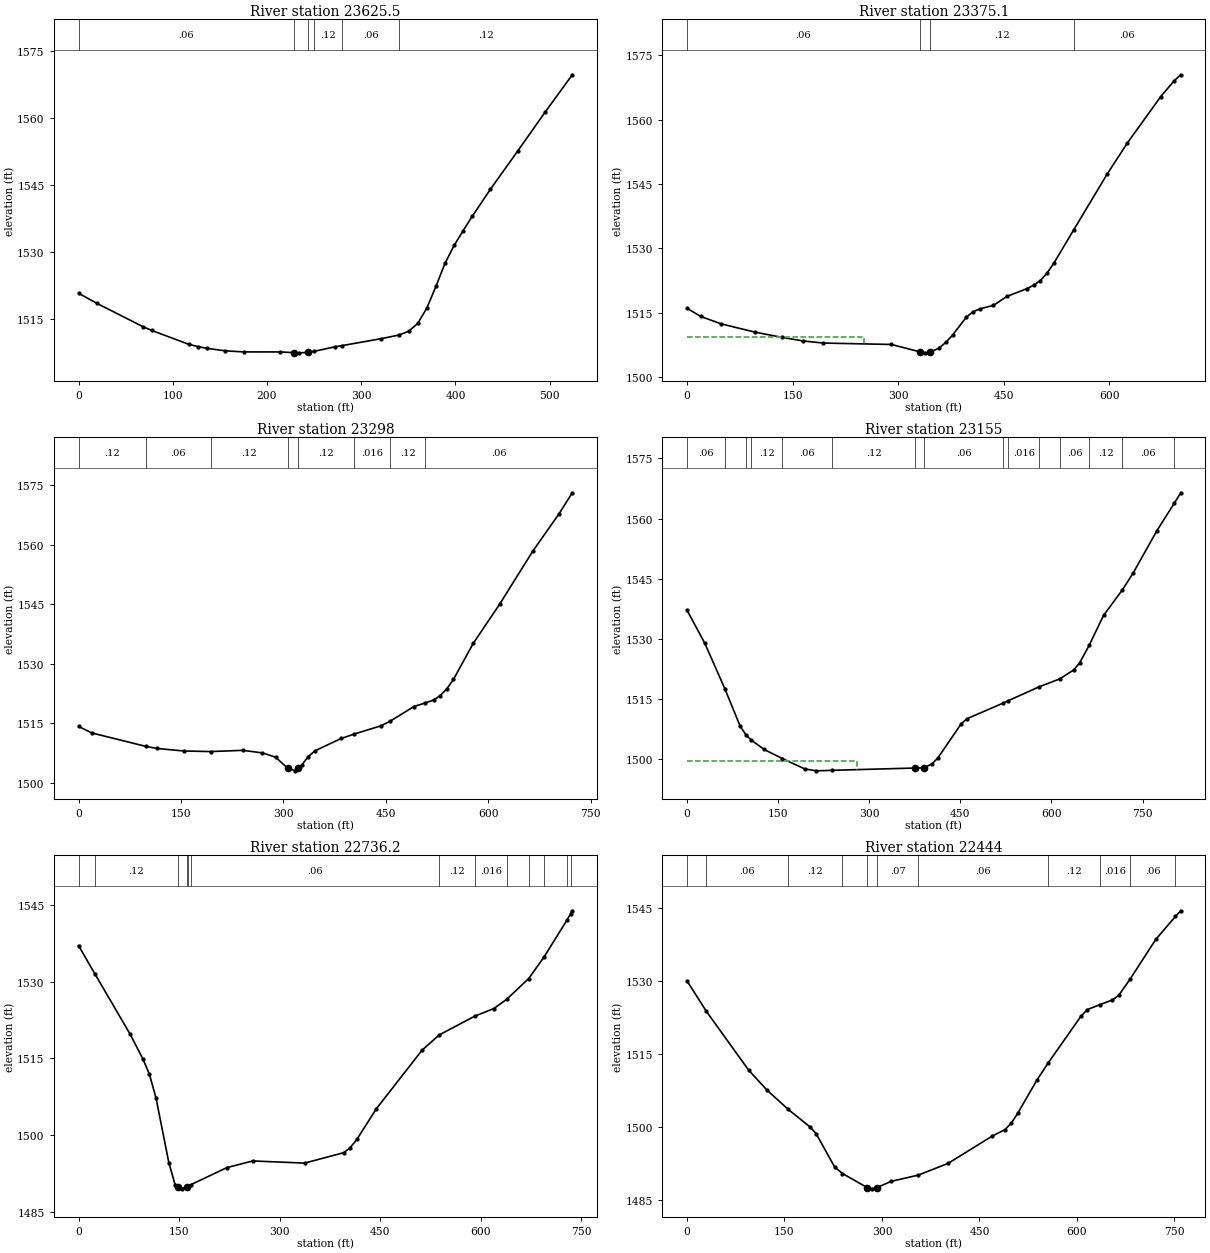
Type RM Length L Ch R = 1 ,23625.5 ,229.4,250.4,266.3
XS GIS Cut Line= 3
     1868114.977      262820.623     1867917.061      263109.686
     1867855.429      263272.012
#Sta/Elev= 30
       0  1520.8    19.5 1518.54    68.1 1513.35    77.8 1512.47   116.8 1509.39
   126.5 1508.88   136.2 1508.48   155.7 1507.92   175.2 1507.68   214.1 1507.67
  228.631507.516   233.6 1507.47   243.3 1507.56  250.021507.805   272.5 1508.84
  280.011509.096   321.1 1510.64  339.671511.431   350.3 1512.29     360 1514.06
   369.6 1517.48   379.3 1522.33   388.9  1527.5   398.6 1531.49   408.2 1534.82
   417.8 1538.01   437.1 1544.07   466.1 1552.63     495 1561.28     524 1569.68
#Mann= 6 ,-1 , 0
       0     .06       0  228.63    .045       0   243.3     .06       0
  250.02     .12       0  280.01     .06       0  339.67     .12       0
Bank Sta=228.63,243.3
XS Rating Curve= 0 ,0
Exp/Cntr=0.3,0.1

Type RM Length L Ch R = 1 ,23375.1 ,82.2,77,77
XS GIS Cut Line= 3
     1868075.206      262823.155     1867657.512      262945.623
     1867603.693       263206.04
#Sta/Elev= 30
       0 1516.05    19.4 1514.14    48.4 1512.41    96.7 1510.47   135.4 1509.24
   164.4 1508.43   193.5 1507.93   290.2  1507.6   330.4  1505.9   338.6 1505.65
   345.4 1505.82   357.9 1506.74   367.6  1508.1   377.2 1509.77   396.6 1513.94
   406.3 1515.24   415.9 1515.88   435.3 1516.72   454.3 1518.79   482.8 1520.62
   492.3  1521.4   501.8  1522.5   511.2  1524.2   520.8 1526.48  549.281534.321
   596.7  1547.3   625.2 1554.51   672.7 1565.34   691.7 1569.02   701.2 1570.45
#Mann= 4 ,-1 , 0
       0     .06       0   330.4    .045       0   345.4     .12       0
  549.28     .06       0
#XS Ineff= 2 , 0
          250.98 1509.32
Permanent Ineff=
       F       F
Bank Sta=330.4,345.4
XS Rating Curve= 0 ,0
Exp/Cntr=0.3,0.1

Type RM Length L Ch R = 1 ,23298   ,160.9,143,124.4
XS GIS Cut Line= 3
     1868014.283      262763.332     1867635.811      262874.443
     1867569.838      263196.491
#Sta/Elev= 30
       0 1514.26    19.2 1512.62   99.081509.205   115.4  1508.7   153.9 1508.07
  193.331507.923   240.5 1508.23   269.4 1507.59   288.6 1506.51  306.591503.696
   317.5 1503.07  321.43 1503.68   327.1 1504.57   336.7 1506.68   346.3 1508.12
   384.8 1511.22  403.651512.326   442.8  1514.4  456.451515.563   491.1 1519.25
  508.021520.178   520.1  1520.9   529.8 1522.03   539.5 1523.73   549.1 1526.08
   578.2 1535.18   616.8 1545.03   665.2 1558.35   703.8  1567.8   723.2 1573.08
#Mann= 8 ,-1 , 0
       0     .12       0   99.08     .06       0  193.33     .12       0
  306.59    .045       0  321.43     .12       0  403.65    .016       0
  456.45     .12       0  508.02     .06       0
Bank Sta=306.59,321.43
XS Rating Curve= 0 ,0
Exp/Cntr=0.3,0.1

Type RM Length L Ch R = 1 ,23155   ,444.8,418.8,391.5
XS GIS Cut Line= 4
     1867843.435      262466.384     1867709.595      262563.679
     1867580.255      262807.603     1867546.401      263177.394
#Sta/Elev= 30
       0 1537.19    29.2 1528.98   62.221517.657    87.6 1508.27    97.51506.051
  105.521504.881   126.5 1502.53  156.931500.214     194 1497.64   213.1 1497.16
  239.17 1497.29   374.9 1497.86  390.241497.873   403.5 1498.92     413 1500.35
   451.3 1508.84   461.1 1510.15  520.251514.009  528.761514.617  580.151518.114
  613.571520.043     637 1522.33   646.8 1524.12  662.321528.466   685.9 1535.89
  716.811542.227   734.7 1546.47   773.8    1557  802.331563.824   812.9 1566.42
#Mann= 15 ,-1 , 0
       0     .06       0   62.22     .12       0    97.5     .08       0
  105.52     .12       0  156.93     .06       0  239.17     .12       0
   374.9    .045       0  390.24     .06       0  520.25     .08       0
  528.76    .016       0  580.15     .12       0  613.57     .06       0
  662.32     .12       0  716.81     .06       0  802.33     .12       0
#XS Ineff= 2 , 0
          279.67 1499.73
Permanent Ineff=
       F       F
Bank Sta=374.9,390.24
XS Rating Curve= 0 ,0
Exp/Cntr=0.3,0.1

Type RM Length L Ch R = 1 ,22736.2 ,295,292.2,288.9
XS GIS Cut Line= 3
     1867185.883      262442.947     1867382.498      262679.926
     1867450.206      263103.103
#Sta/Elev= 30
       0 1537.02   24.161531.546      77 1519.72    96.2 1514.85   105.8 1511.88
   115.5 1507.31   134.7 1494.67   144.3 1490.25  147.781490.007     154 1489.57
  162.071489.998  163.861490.099  168.021490.411   221.3 1493.71   259.8 1495.01
   337.1 1494.59   395.6 1496.62   405.3 1497.62   415.1  1499.2   444.3 1505.21
   512.5 1516.62  537.89 1519.58  591.221523.258   619.6 1524.74  638.571526.525
   671.41530.578  694.571534.834  728.761542.031   734.11543.251   736.5  1543.8
#Mann= 13 ,-1 , 0
       0     .06       0   24.16     .12       0  147.78    .045       0
  162.07     .12       0  163.86     .07       0  168.02     .06       0
  537.89     .12       0  591.22    .016       0  638.57     .12       0
   671.4     .06       0  694.57     .12       0  728.76     .06       0
   734.1     .12       0
Bank Sta=147.78,162.07
XS Rating Curve= 0 ,0
Exp/Cntr=0.3,0.1

Type RM Length L Ch R = 1 ,22444   ,413.5,438.2,456.5
XS GIS Cut Line= 4
     1867047.862      262483.311     1867042.654      262729.405
     1867334.321      263001.541     1867351.248      263114.822
#Sta/Elev= 30
       0 1530.09   29.571523.871    94.7 1511.75   123.1 1507.62  155.821503.637
   189.4 1500.04   198.8 1498.63   227.2  1491.8  239.26 1490.46   277.1 1487.58
   285.1 1487.31   292.1 1487.56   314.3 1488.86  355.541490.122   401.8 1492.55
   469.9 1498.19   489.4  1499.5   499.1 1500.85   508.8 1502.84     538  1509.6
  556.111513.291   606.1  1522.8   615.9 1524.17  635.641525.214   654.6 1526.17
   664.2  1527.1  681.451530.397   721.4 1538.64  751.451543.337   759.6  1544.5
#Mann= 11 ,-1 , 0
       0     .12       0   29.57     .06       0  155.82     .12       0
  239.26     .07       0   277.1    .045       0   292.1     .07       0
  355.54     .06       0  556.11     .12       0  635.64    .016       0
  681.45     .06       0  751.45     .12       0
Bank Sta=277.1,292.1
XS Rating Curve= 0 ,0
Exp/Cntr=0.3,0.1

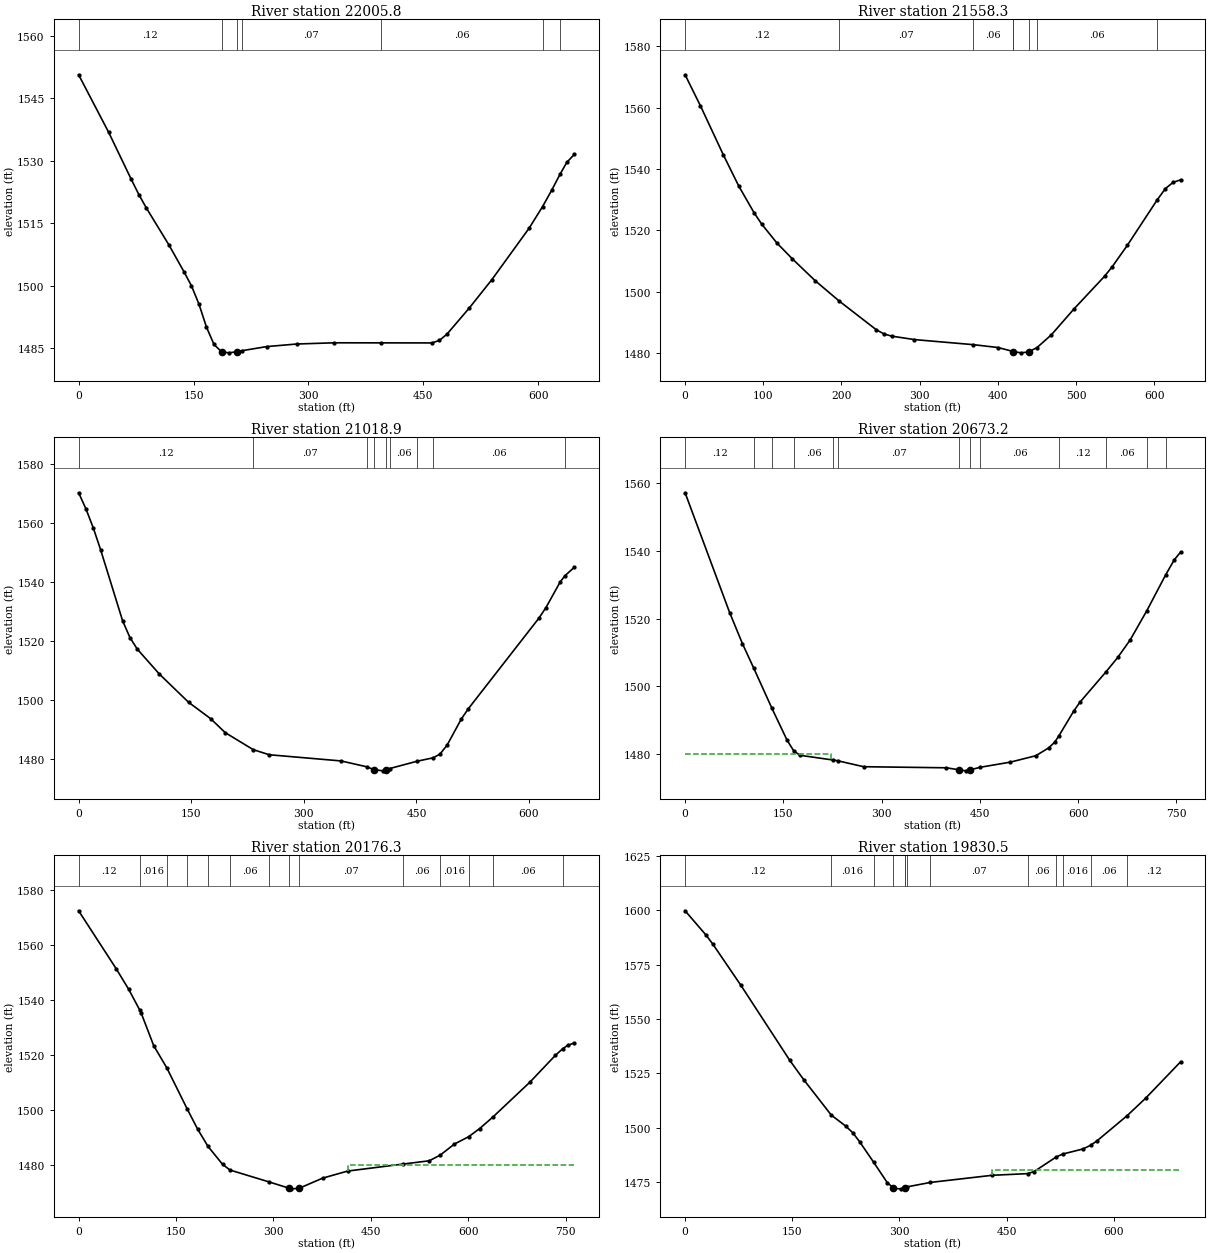
Type RM Length L Ch R = 1 ,22005.8 ,454.2,447.5,439.7
XS GIS Cut Line= 3
     1866805.675      262483.311     1866792.654      262885.655
     1866825.206      263127.843
#Sta/Elev= 30
       0  1550.6    39.3 1536.75    68.7 1525.49    78.6 1521.85    88.4 1518.62
   117.8 1509.77   137.5 1503.32   147.3 1499.93   157.1 1495.53   166.9 1490.01
   176.7 1485.86   186.6 1484.08   196.4 1483.84   206.2 1484.11  213.071484.348
   245.5 1485.34   284.7 1485.96   333.8 1486.25  394.281486.235   461.2 1486.22
     471 1486.83   480.8 1488.32   510.1 1494.63   539.4  1501.4   588.3 1513.82
  605.691518.968   617.6  1522.9  628.371526.685   637.2 1529.55   646.9 1531.46
#Mann= 7 ,-1 , 0
       0     .12       0   186.6    .045       0   206.2     .12       0
  213.07     .07       0  394.28     .06       0  605.69     .12       0
  628.37    .016       0
Bank Sta=186.6,206.2
XS Rating Curve= 0 ,0
Exp/Cntr=0.3,0.1

Type RM Length L Ch R = 1 ,21558.3 ,524.9,539.4,552
XS GIS Cut Line= 3
     1866385.102       262582.27     1866499.685       262776.28
     1866619.477      263166.905
#Sta/Elev= 30
       0 1570.76    19.6 1560.65      49 1544.61    68.6  1534.5    88.2 1525.78
      98 1522.06   117.6 1515.86   137.2 1510.74   166.5 1503.59  197.32 1496.94
   244.8 1487.58   254.5 1486.25   264.2 1485.54   293.4 1484.41  368.621482.759
   400.4 1481.82  419.481480.542   419.9 1480.51   429.6 1480.09   439.3 1480.38
  450.221481.813   468.5 1485.96   497.7 1494.47   536.6 1505.07   546.4 1508.18
   565.8 1515.18  603.921529.968   614.4 1533.64   624.2 1535.67   633.9  1536.5
#Mann= 8 ,-1 , 0
       0     .12       0  197.32     .07       0  368.62     .06       0
  419.48     .12       0   419.9    .045       0   439.3     .12       0
  450.22     .06       0  603.92     .12       0
Bank Sta=419.9,439.3
XS Rating Curve= 0 ,0
Exp/Cntr=0.3,0.1

Type RM Length L Ch R = 1 ,21018.9 ,355.4,345.7,335.5
XS GIS Cut Line= 4
     1866184.581      262617.426     1866180.675      262910.395
     1866131.196      263101.801     1866153.331       263269.77
#Sta/Elev= 30
       0 1570.13     9.8 1564.65    19.5 1558.26    29.3 1550.85    58.6 1526.83
    68.4 1521.15    78.1 1517.27   107.4 1508.87   146.5 1499.28   175.8 1493.76
   195.3 1489.02  232.571483.276   253.9 1481.55   349.5 1479.46  383.541477.497
  393.931476.478     406 1476.11  409.121476.403  414.181476.876  451.291479.383
   472.31480.516   481.3 1481.77   490.7 1484.74   509.5 1493.52   518.9 1497.04
     613  1527.7   622.5 1531.31   641.3  1539.9  647.781542.078   660.1 1544.89
#Mann= 9 ,-1 , 0
       0     .12       0  232.57     .07       0  383.54     .12       0
  393.93    .045       0  409.12     .12       0  414.18     .06       0
  451.29     .12       0   472.3     .06       0  647.78    .016       0
Bank Sta=393.93,409.12
XS Rating Curve= 0 ,0
Exp/Cntr=0.3,0.1

Type RM Length L Ch R = 1 ,20673.2 ,506.2,496.9,480.9
XS GIS Cut Line= 4
      1865921.56      262607.009     1865849.946      262787.999
     1865908.539      263143.468     1866014.008      263315.343
#Sta/Elev= 30
       0 1557.18    68.1 1521.74    87.6 1512.58  104.91 1505.32  132.451493.548
   155.7 1484.08  165.671480.981   175.2 1479.62   226.21478.207  232.991477.999
   272.5 1476.24   399.1 1475.92   418.6 1475.31   428.3 1475.02  434.561475.291
  450.951476.083   496.5 1477.59   535.4 1479.48   554.9 1481.77   564.5 1483.52
  570.711485.357   593.3 1492.65   602.9 1495.31  642.811504.311   660.5 1508.51
   679.7 1513.74  705.09 1522.38  733.91 1532.99     747 1537.41   756.6 1539.66
#Mann= 13 ,-1 , 0
       0     .12       0  104.91     .08       0  132.45     .12       0
  165.67     .06       0   226.2     .12       0  232.99     .07       0
   418.6    .045       0  434.56     .07       0  450.95     .06       0
  570.71     .12       0  642.81     .06       0  705.09     .12       0
  733.91    .016       0
#XS Ineff= 2 , 0
          222.91  1480.1
Permanent Ineff=
       F       F
Bank Sta=418.6,434.56
XS Rating Curve= 0 ,0
Exp/Cntr=0.3,0.1

Type RM Length L Ch R = 1 ,20176.3 ,349.6,345.8,342.1
XS GIS Cut Line= 4
       1865196.3      263015.864     1865404.633      263091.384
     1865598.643      263264.561     1865834.321      263418.207
#Sta/Elev= 30
       0 1572.42    57.8  1551.4    77.1 1543.92   93.781536.521    96.4 1535.26
   115.6 1523.47  135.911515.354  167.521500.333   183.1 1493.25  199.131486.936
   221.6 1480.42  233.091478.337  293.041474.044   324.6 1471.71   327.6 1471.52
   339.6 1471.73   375.7  1475.4   414.2 1477.97  499.531480.512   539.9  1481.7
  556.981483.797   578.7 1487.79  600.531490.436   617.5 1493.39  638.471497.712
   695.1 1510.29   733.9 1519.92  745.341522.363   753.3 1523.61     763 1524.44
#Mann= 14 ,-1 , 0
       0     .12       0   93.78    .016       0  135.91     .12       0
  167.52    .016       0  199.13     .12       0  233.09     .06       0
  293.04     .07       0   324.6    .045       0   339.6     .07       0
  499.53     .06       0  556.98    .016       0  600.53     .12       0
  638.47     .06       0  745.34    .016       0
#XS Ineff= 2 , 0
                          414.45         1480.07
Permanent Ineff=
       F       F
Bank Sta=324.6,339.6
XS Rating Curve= 0 ,0
Exp/Cntr=0.3,0.1

Type RM Length L Ch R = 1 ,19830.5 ,198.4,179.3,159.3
XS GIS Cut Line= 2
     1865039.674      263290.241     1865627.781       263658.08
#Sta/Elev= 30
       0  1599.8    29.3 1588.63    39.1 1584.34    78.2 1565.47   146.6 1530.99
   166.1 1522.11  204.651505.852   224.7 1500.83   234.5 1497.81   244.2 1493.66
  263.891484.205   283.3 1474.64  291.261472.543   293.1 1472.06   302.5 1471.94
  308.06 1472.52  308.261472.542   311.31472.884  343.47 1474.89   429.9 1478.17
  479.38 1478.93   488.5 1479.87   519.51486.592  528.361487.911   556.9 1490.27
  567.651491.955   576.4 1493.94  618.831505.602   644.8 1513.65   693.7 1530.37
#Mann= 13 ,-1 , 0
       0     .12       0  204.65    .016       0  263.89     .12       0
  291.26    .045       0  308.06     .12       0  308.26     .08       0
   311.3     .06       0  343.47     .07       0  479.38     .06       0
   519.5     .08       0  528.36    .016       0  567.65     .06       0
  618.83     .12       0
#XS Ineff= 2 , 0
                          429.82         1480.81
Permanent Ineff=
       F       F
Bank Sta=291.26,308.06
XS Rating Curve= 0 ,0
Exp/Cntr=0.3,0.1

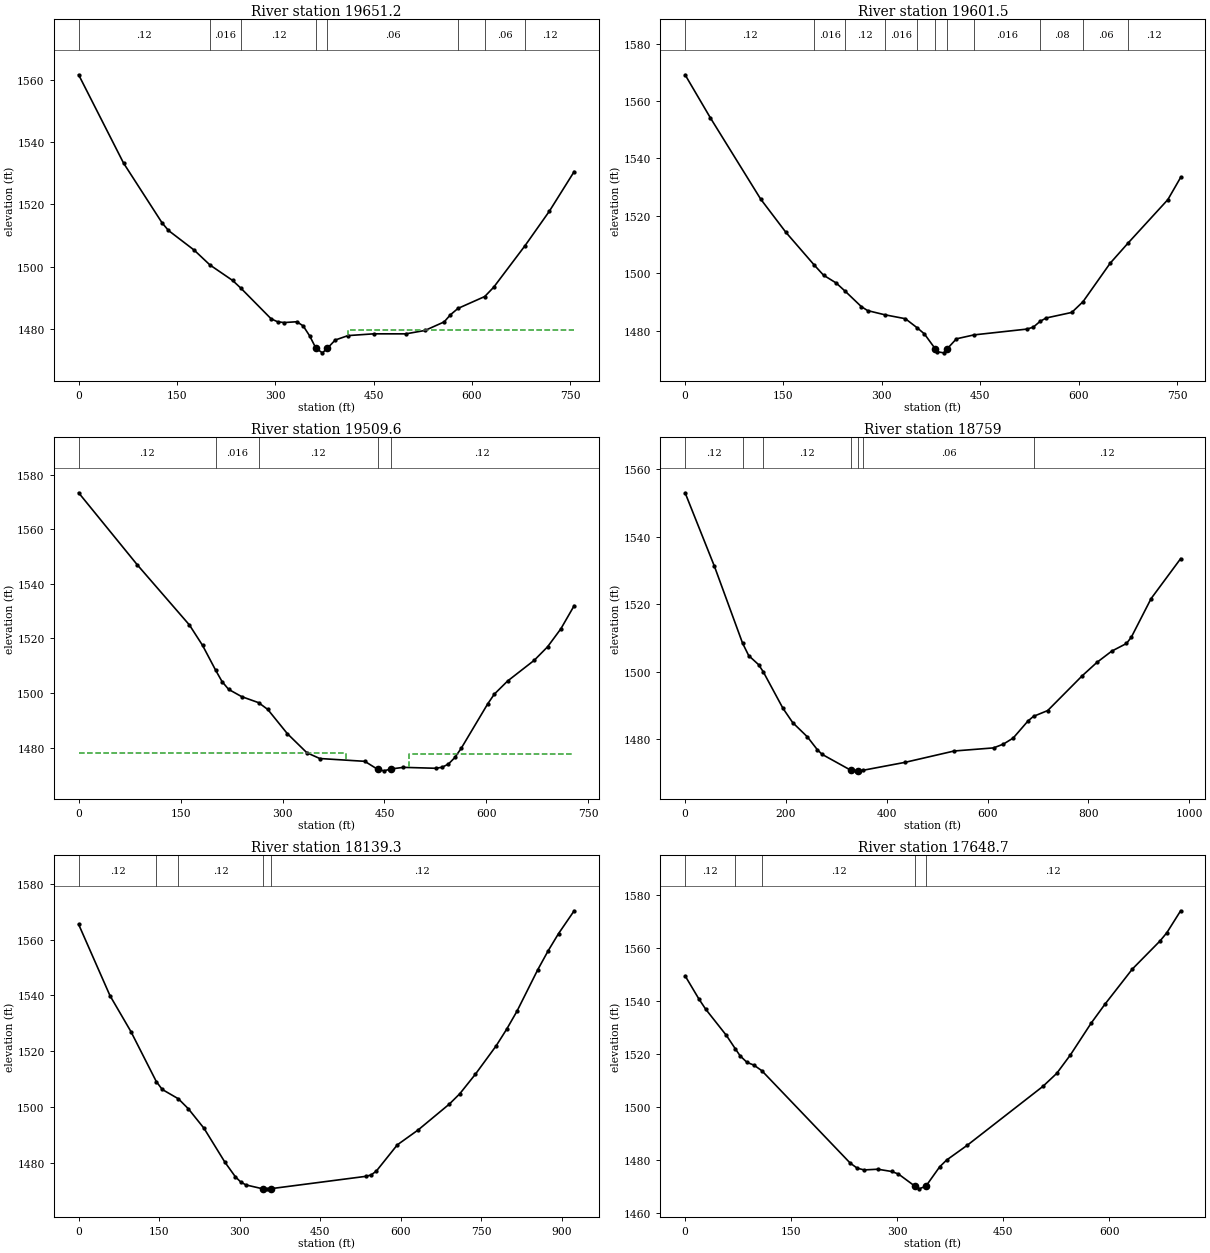
Type RM Length L Ch R = 1 ,19651.2 ,49.6,49.7,49.6
XS GIS Cut Line= 4
     1864958.293      263455.172     1865241.496      263629.868
     1865455.255      263560.424     1865621.271      263668.931
#Sta/Elev= 30
       0 1561.74    68.5 1533.31   127.2 1514.08     137 1511.61   176.2 1505.29
  200.35 1500.49   234.9 1495.51  247.741492.973   293.6 1483.16   303.4 1482.22
   313.2 1481.96   332.8 1482.22   342.5 1480.88   352.3 1477.69   362.1 1473.63
   371.8 1472.21  379.181473.639   391.4 1476.34   410.9 1477.76     450 1478.33
   498.9 1478.32   528.2 1479.41   557.5 1482.17     567 1484.45  578.521486.504
  619.411490.344   633.1 1493.35  681.011506.762   718.1 1517.86   755.8 1530.57
#Mann= 8 ,-1 , 0
       0     .12       0  200.35    .016       0  247.74     .12       0
   362.1    .045       0  379.18     .06       0  578.52    .016       0
  619.41     .06       0  681.01     .12       0
#XS Ineff= 2 , 0
                          410.32         1479.46
Permanent Ineff=
       F       F
Bank Sta=362.1,379.18
XS Rating Curve= 0 ,0
Exp/Cntr=0.3,0.1

Type RM Length L Ch R = 1 ,19601.5 ,85.3,91.9,98.6
XS GIS Cut Line= 4
     1864942.017      263493.149     1865244.752      263678.696
      1865458.51      263609.252      1865606.08      263704.738
#Sta/Elev= 30
       0 1569.13    38.4 1554.19   115.2 1525.86   153.5 1514.33  197.151502.819
   211.1 1499.35   230.3 1496.64  244.461493.694   268.7 1488.41   278.3 1487.02
  304.151485.581   335.9 1484.19  354.341480.943   364.8 1478.92  381.781473.606
   384.4  1472.7   394.2 1472.31  399.221473.614   413.7 1477.19  440.55 1478.56
   521.2 1480.58     531 1481.26   541.41483.289   550.5 1484.44   589.6 1486.38
  606.71 1490.11   648.2 1503.53  675.561510.561   736.1 1525.66   755.6 1533.39
#Mann= 11 ,-1 , 0
       0     .12       0  197.15    .016       0  244.46     .12       0
  304.15    .016       0  354.34     .12       0  381.78    .045       0
  399.22     .12       0  440.55    .016       0   541.4     .08       0
  606.71     .06       0  675.56     .12       0
Bank Sta=381.78,399.22
XS Rating Curve= 0 ,0
Exp/Cntr=0.3,0.1

Type RM Length L Ch R = 1 ,19509.6 ,727.9,750.6,771.1
XS GIS Cut Line= 4
     1864888.849      263577.785     1865168.797      263763.332
     1865405.342      263756.821     1865557.252      263794.799
#Sta/Elev= 30
       0 1573.42    86.4 1546.97   163.1 1524.91   182.3 1517.47  201.671508.315
   211.1 1504.15   220.7 1501.33   239.9 1498.66  264.711496.458   278.3 1493.96
   307.1 1485.08   335.8 1478.09   354.8 1475.97     421 1474.94     440    1472
   449.4 1471.45   458.9 1472.11   477.8 1472.73   525.2 1472.39   534.6 1472.74
   544.1 1473.94   553.6 1476.35     563 1479.75   601.8 1495.97   611.6 1499.57
   631.2  1504.4   670.4    1512   689.9 1516.92   709.5 1523.53   729.1 1532.02
#Mann= 5 ,-1 , 0
       0     .12       0  201.67    .016       0  264.71     .12       0
     440    .045       0   458.9     .12       0
#XS Ineff= 2 , 0
          393.81 1477.84  485.45         1477.64
Permanent Ineff=
       F       F
Bank Sta=440,458.9
XS Rating Curve= 0 ,0
Exp/Cntr=0.3,0.1

Type RM Length L Ch R = 1 ,18759   ,561.6,619.7,622.9
XS GIS Cut Line= 3
     1864747.081      263794.509     1865075.206      264239.822
     1865504.893      264247.634
#Sta/Elev= 30
       0 1553.04    58.2 1531.24  113.961508.483   126.2 1504.78   145.6 1502.13
  154.811500.051   194.1 1489.17   213.5 1484.92   242.6  1480.7     262 1476.96
   271.7 1475.53   328.5 1470.83   339.6 1470.64   343.5 1470.68  353.531470.825
   436.7 1473.17   533.7 1476.52   611.8 1477.44   631.3 1478.56   650.8 1480.36
   680.1 1485.41  691.071486.788   719.2  1488.5   787.6  1498.8   816.9 1502.78
   846.2 1506.11   875.5 1508.38   885.2 1510.28   924.3 1521.68   982.9 1533.52
#Mann= 7 ,-1 , 0
       0     .12       0  113.96    .016       0  154.81     .12       0
   328.5    .045       0   343.5     .12       0  353.53     .06       0
  691.07     .12       0
Bank Sta=328.5,343.5
XS Rating Curve= 0 ,0
Exp/Cntr=0.3,0.1

Type RM Length L Ch R = 1 ,18139.3 ,487.9,490.6,493.7
XS GIS Cut Line= 3
     1864478.852      263959.874     1864683.279      264496.332
     1864654.633      264843.989
#Sta/Elev= 30
       0 1565.47    58.4  1539.9    97.3 1527.05  144.671509.094   155.7 1506.27
  185.861502.906   204.3 1499.35   233.5 1492.34   272.4 1480.19   291.9 1474.96
   301.6 1473.14   311.4 1472.04   342.7 1470.65   350.3 1470.63   357.7 1470.68
   535.2 1475.12   544.9 1475.62   554.6 1477.03   593.5  1486.4   632.2 1491.73
   690.4 1501.02   709.8 1504.71   738.8  1511.7   777.6 1521.91     797 1527.82
   816.3  1534.3   855.1 1549.21   874.5 1556.01   893.8 1562.17   922.9 1570.34
#Mann= 5 ,-1 , 0
       0     .12       0  144.67    .016       0  185.86     .12       0
   342.7    .045       0   357.7     .12       0
Bank Sta=342.7,357.7
XS Rating Curve= 0 ,0
Exp/Cntr=0.3,0.1

Type RM Length L Ch R = 1 ,17648.7 ,377.5,378.1,378.5
XS GIS Cut Line= 2
     1864148.991      264200.759     1864314.355      264881.749
#Sta/Elev= 30
       0 1549.53    19.5 1540.77    29.2 1536.87    58.4 1526.98   71.031521.915
    77.9 1519.23    87.6 1516.77    97.3 1515.75  108.57 1513.62   233.6 1478.66
   243.3 1476.79   253.1  1476.1   272.5 1476.37     292 1475.52   301.7 1474.56
   325.5 1469.86   330.9 1468.95   340.5 1469.94   360.1  1477.3   369.9 1479.85
   399.1 1485.44   506.1 1507.72   525.6 1512.63     545 1519.64   574.2  1531.6
   593.7 1538.76   632.6 1552.11   671.6 1562.69   681.3 1565.83   700.8 1574.12
#Mann= 5 ,-1 , 0
       0     .12       0   71.03    .016       0  108.57     .12       0
   325.5    .045       0   340.5     .12       0
Bank Sta=325.5,340.5
XS Rating Curve= 0 ,0
Exp/Cntr=0.3,0.1

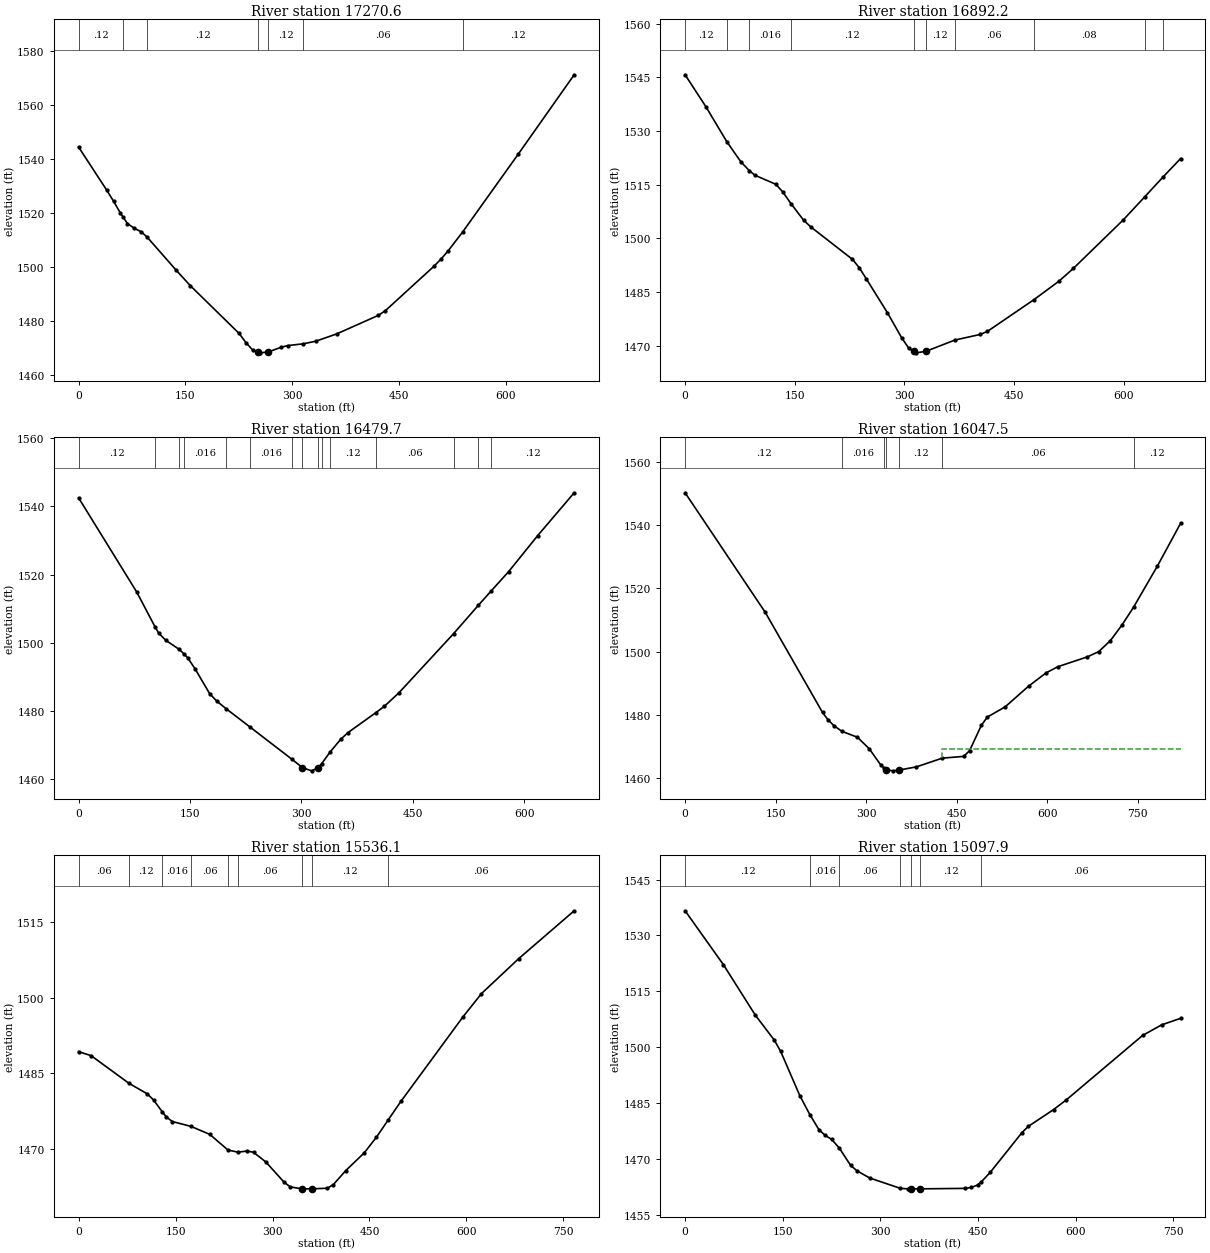
Type RM Length L Ch R = 1 ,17270.6 ,373,378.5,383.4
XS GIS Cut Line= 3
     1863816.525      264301.454     1863903.765      264693.381
     1864095.171      264917.339
#Sta/Elev= 30
       0 1544.47    39.2 1528.64      49 1524.46    58.8 1519.98   62.16 1518.67
    68.6 1516.16    78.4 1514.37    88.1 1513.09   96.611511.023   137.1 1498.86
   156.7 1493.21   225.2 1475.52     235  1472.1   244.8  1469.2   251.5 1468.57
   254.6 1468.28   266.5 1468.61     284  1470.3   293.8 1470.97  315.26 1471.61
     333 1472.58   362.4 1475.28   421.2 1482.18     431 1483.92   499.7 1500.48
   509.5 1503.13   519.4 1506.17   539.51513.062   617.6 1541.89   696.1 1571.26
#Mann= 7 ,-1 , 0
       0     .12       0   62.16    .016       0   96.61     .12       0
   251.5    .045       0   266.5     .12       0  315.26     .06       0
   539.5     .12       0
Bank Sta=251.5,266.5
XS Rating Curve= 0 ,0
Exp/Cntr=0.3,0.1

Type RM Length L Ch R = 1 ,16892.2 ,403.3,412.5,421.6
XS GIS Cut Line= 3
     1863495.779      264342.686     1863512.706      264618.728
     1863510.102       265019.77
#Sta/Elev= 30
       0 1545.74    28.6 1536.76   57.131527.004    76.3 1521.39   87.951518.917
    95.4 1517.66     124 1515.13   133.5 1513.01  144.651509.749   162.1 1505.07
   171.7 1503.24   228.9 1494.13   238.4 1491.73     248 1488.63   276.6 1479.24
   296.1 1472.22   305.9 1469.28  312.451468.425   315.7    1468  329.171468.411
  368.691471.562   403.7 1473.15   413.5 1474.01  476.931482.855   511.3 1488.05
   530.9  1491.6   599.4 1505.22  628.361511.583  653.671517.192   677.6 1522.33
#Mann= 10 ,-1 , 0
       0     .12       0   57.13     .08       0   87.95    .016       0
  144.65     .12       0  312.45    .045       0  329.17     .12       0
  368.69     .06       0  476.93     .08       0  628.36     .12       0
  653.67     .08       0
Bank Sta=312.45,329.17
XS Rating Curve= 0 ,0
Exp/Cntr=0.3,0.1

Type RM Length L Ch R = 1 ,16479.7 ,437.5,432.2,399.6
XS GIS Cut Line= 3
      1863227.55      264353.537     1863063.487      264731.141
     1863051.768       264986.35
#Sta/Elev= 30
       0 1542.49    78.4 1514.83  102.731504.729   107.8 1502.82   117.6 1500.68
   135.31498.095  141.32 1496.85     147 1495.54   156.8 1492.35   176.4 1485.08
   186.2 1482.84  198.961480.605  230.911475.266  287.251465.828  301.391463.369
   313.7 1462.44   322.5 1463.35  327.241464.545  338.531467.948   352.9 1471.71
   362.7 1473.66   400.41479.543   411.7 1481.38   431.4 1485.36  504.951502.706
  538.161510.986  555.471515.209   578.8 1520.83     618 1531.42   667.2    1544
#Mann= 15 ,-1 , 0
       0     .12       0  102.73    .016       0   135.3     .12       0
  141.32    .016       0  198.96     .12       0  230.91    .016       0
  287.25     .12       0  301.39    .045       0   322.5     .12       0
  327.24     .06       0  338.53     .12       0   400.4     .06       0
  504.95     .12       0  538.16     .06       0  555.47     .12       0
Bank Sta=301.39,322.5
XS Rating Curve= 0 ,0
Exp/Cntr=0.3,0.1

Type RM Length L Ch R = 1 ,16047.5 ,503.5,511.4,538.4
XS GIS Cut Line= 4
     1862934.581      264232.009     1862736.664       264394.77
     1862715.831      264687.739      1862796.56      264946.853
#Sta/Elev= 30
       0 1550.19   132.9 1512.42   227.8 1480.82   237.3  1478.4   246.8 1476.63
  259.831474.862   285.6    1473   305.2 1469.36   324.8 1464.12  329.211463.399
  333.321462.728   344.4 1462.38   354.2 1462.61   383.5 1463.64  426.341466.393
   461.8 1466.94   471.6 1468.77   491.2 1476.79     501 1479.37   530.4 1482.57
   569.3 1489.11   598.4 1493.32   617.8 1495.26   666.3 1498.34   685.6 1500.02
     705 1503.51   724.4 1508.49  743.391514.065   782.6 1526.95   821.4 1540.57
#Mann= 7 ,-1 , 0
       0     .12       0  259.83    .016       0  329.21     .12       0
  333.32    .045       0   354.2     .12       0  426.34     .06       0
  743.39     .12       0
#XS Ineff= 2 , 0
                          426.21         1469.29
Permanent Ineff=
       F       F
Bank Sta=333.32,354.2
XS Rating Curve= 0 ,0
Exp/Cntr=0.3,0.1

Type RM Length L Ch R = 1 ,15536.1 ,452.6,438.2,424.2
XS GIS Cut Line= 4
     1862256.196      264159.093     1862346.039      264414.301
     1862288.748      264605.707     1862267.914       264901.28
#Sta/Elev= 30
       0 1489.28    19.3 1488.49   77.781483.013   106.3  1480.9     116 1479.68
  129.591477.312   135.3 1476.37   144.9 1475.42  173.711474.457   202.9 1472.87
  231.051469.766  246.231469.339   260.9 1469.56   270.6 1469.31   289.6  1467.4
   318.1 1463.35   327.6 1462.44   345.3 1462.06   360.3 1462.06   384.7 1462.18
   394.2 1462.92   413.3 1465.68   441.8 1469.19   460.8 1472.31  478.541475.662
     499 1479.48   594.6 1496.18   623.3 1500.81   680.6 1507.71   766.7 1517.24
#Mann= 9 ,-1 , 0
       0     .06       0   77.78     .12       0  129.59    .016       0
  173.71     .06       0  231.05     .12       0  246.23     .06       0
   345.3    .045       0   360.3     .12       0  478.54     .06       0
Bank Sta=345.3,360.3
XS Rating Curve= 0 ,0
Exp/Cntr=0.3,0.1

Type RM Length L Ch R = 1 ,15097.9 ,373.5,378.5,373
XS GIS Cut Line= 3
     1861805.675      264195.551     1861941.091      264323.155
     1862152.029      264858.311
#Sta/Elev= 30
       0 1536.64    58.8 1522.17   107.7 1508.64   137.1 1501.86   146.9 1498.83
   176.3 1486.93  191.57 1481.88   205.6 1477.82   215.3 1476.27   225.1 1475.21
  236.951472.865   254.3  1468.2   264.1 1466.76   283.6 1464.82  330.681462.047
   342.1 1461.91   346.4 1461.91   361.4 1461.91   429.8 1462.03   439.6 1462.27
   449.3 1462.94  454.82 1463.74   468.8 1466.34   517.6 1477.04   527.3  1478.7
   566.3 1483.23   585.8 1485.84   702.8 1503.13     732 1505.97   761.3 1507.74
#Mann= 7 ,-1 , 0
       0     .12       0  191.57    .016       0  236.95     .06       0
  330.68     .12       0   346.4    .045       0   361.4     .12       0
  454.82     .06       0
Bank Sta=346.4,361.4
XS Rating Curve= 0 ,0
Exp/Cntr=0.3,0.1