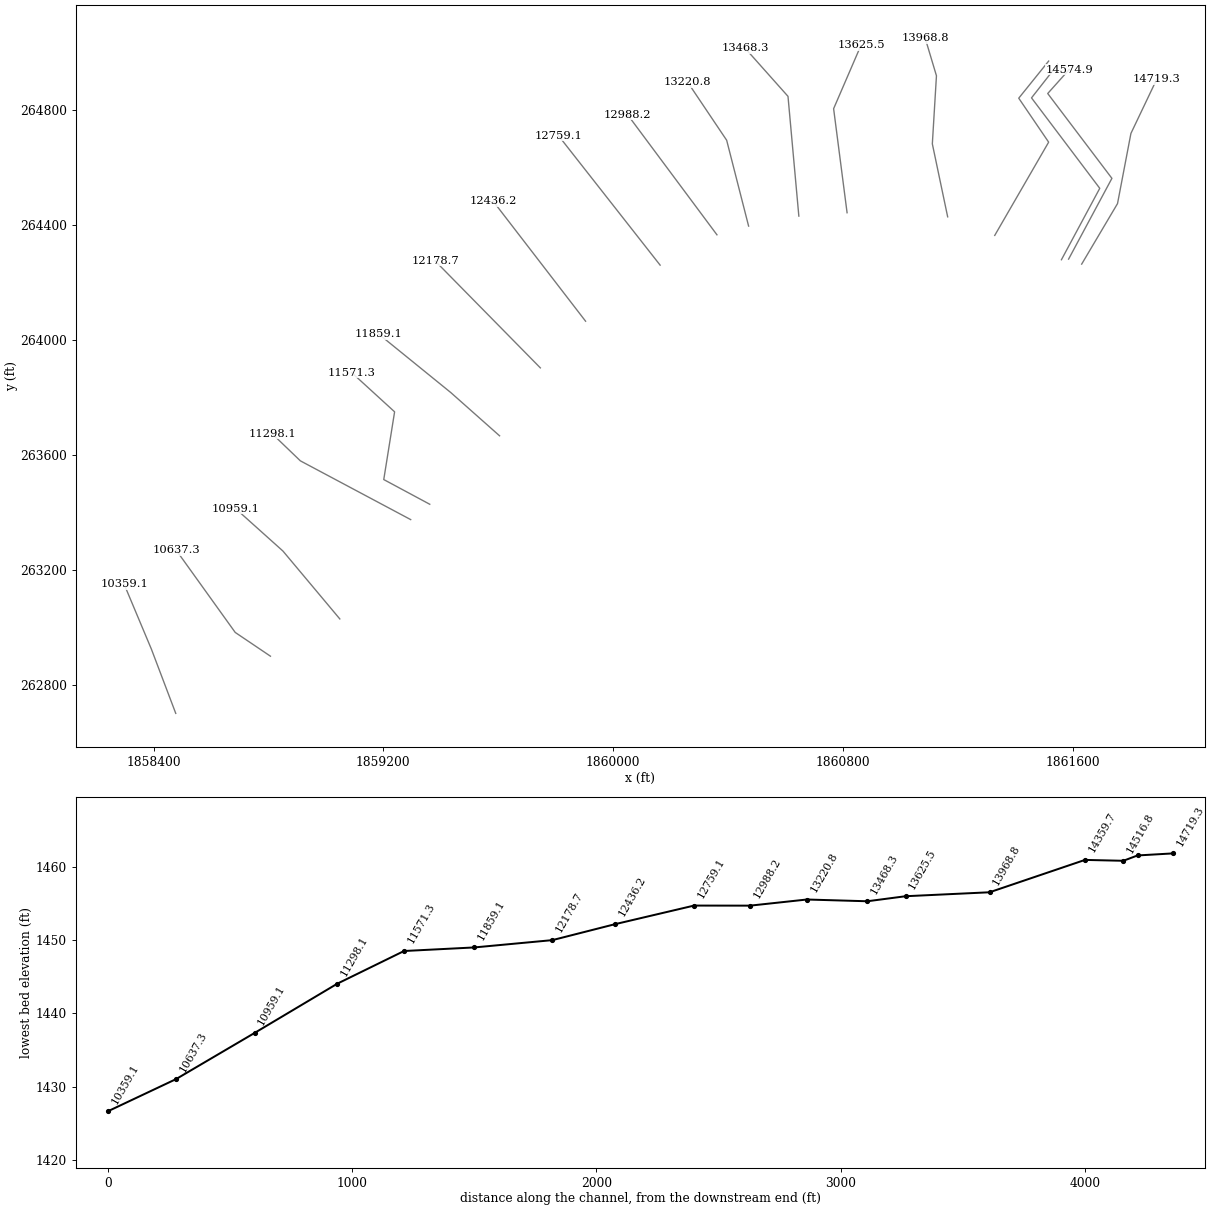
HEC-RAS study RACCOONRN.prj: RACCOONRN

--- RACCOONRN.g01 (geometry) --- (continued)

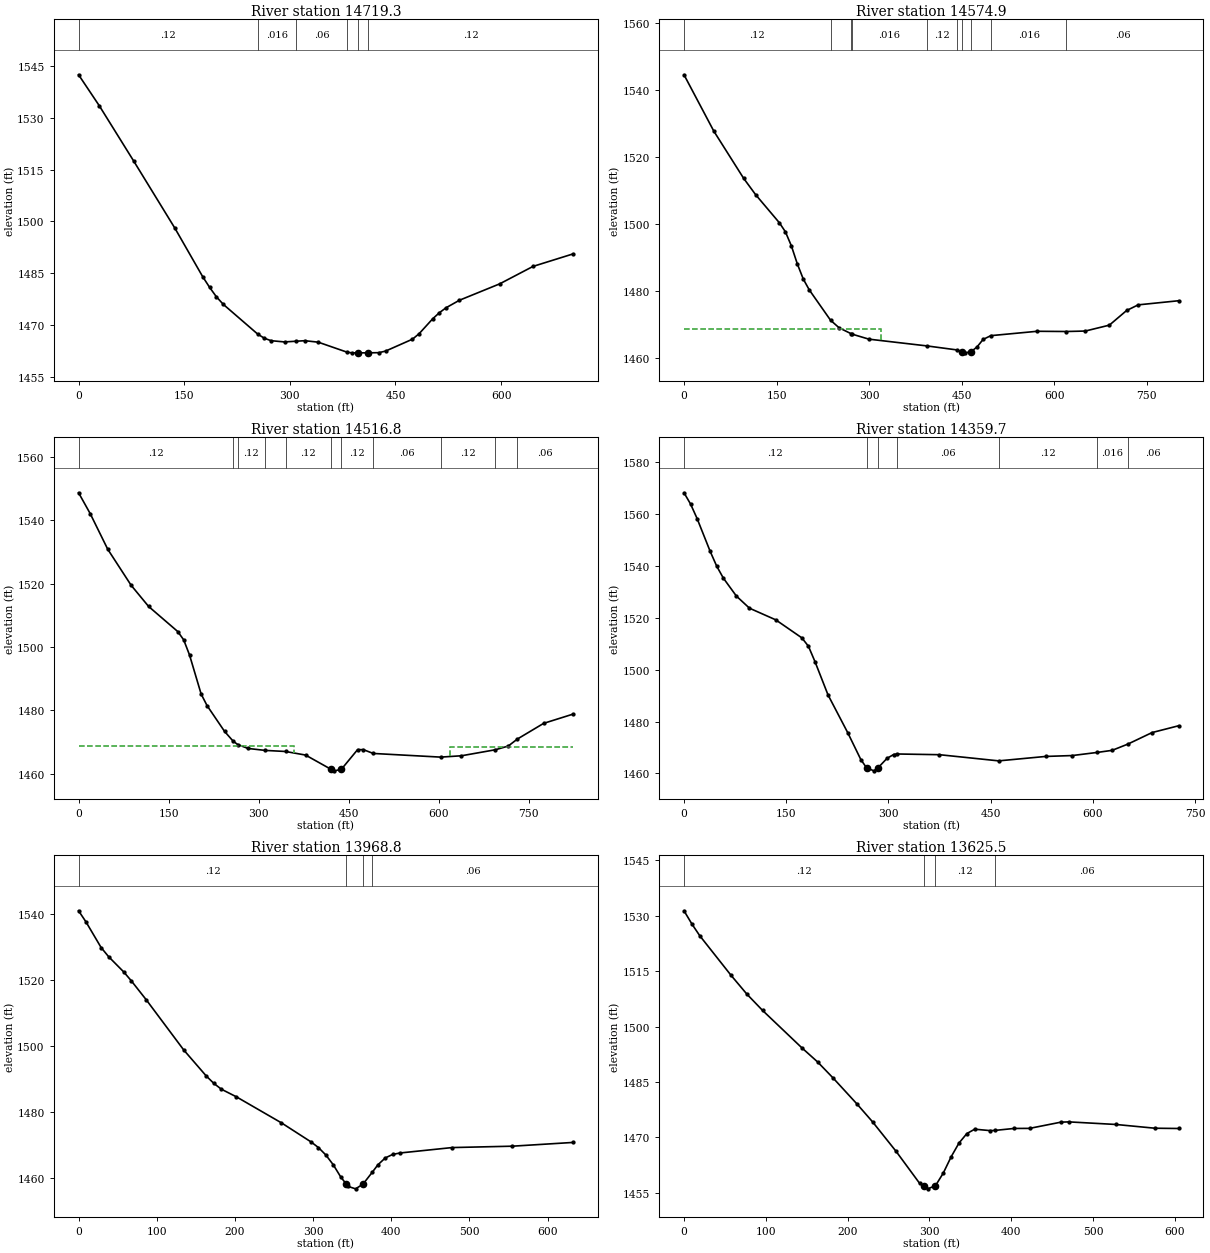
Type RM Length L Ch R = 1 ,14719.3 ,103,144.5,165.5
XS GIS Cut Line= 4
     1861631.687      264262.898      1861756.47      264473.401
     1861803.128      264717.542     1861893.189      264906.344
#Sta/Elev= 30
       0 1542.46    29.4 1533.49    78.3 1517.46     137 1497.94   176.2 1483.99
     186  1480.9   195.8 1478.12   205.6 1475.94  254.411467.336   263.8 1466.14
   273.4 1465.43   292.5 1465.07  308.65 1465.27   321.2 1465.43   340.3    1465
  381.231462.105   388.1 1461.91   396.3 1461.91   411.3 1461.91   426.4 1461.96
   435.9 1462.41   474.2 1465.87   483.7 1467.47   502.8 1471.75   512.3 1473.52
   521.8 1474.96   540.8 1477.14   597.9 1481.88   645.4 1486.95   702.4 1490.58
#Mann= 6 ,-1 , 0
       0     .12       0  254.41    .016       0  308.65     .06       0
  381.23     .12       0   396.3    .045       0   411.3     .12       0
Bank Sta=396.3,411.3
XS Rating Curve= 0 ,0
Exp/Cntr=0.3,0.1

Type RM Length L Ch R = 1 ,14574.9 ,80.2,58.1,55.7
XS GIS Cut Line= 4
     1861586.114      264280.259     1861736.939      264561.292
     1861513.415      264856.431     1861588.285      264939.981
#Sta/Elev= 30
       0 1544.57    48.3 1527.76    96.6 1513.69     116 1508.82   154.6 1500.41
   164.3 1497.73     174 1493.53   183.6 1488.16   193.3 1483.62     203  1480.4
  237.391471.372   251.3  1469.1  270.951467.323  272.51  1467.2   299.6 1465.71
  393.43  1463.7  442.941462.482  449.881462.016   455.4 1461.63   465.1 1461.97
   474.8 1463.39   484.6 1465.62  497.071466.755   572.3 1468.06  619.591467.994
   650.2 1468.13   689.2 1469.89   717.2 1474.26   735.9 1475.94   801.4 1477.17
#Mann= 10 ,-1 , 0
       0     .12       0  237.39     .06       0  270.95     .12       0
  272.51    .016       0  393.43     .12       0  442.94    .016       0
  449.88    .045       0   465.1     .12       0  497.07    .016       0
  619.59     .06       0
#XS Ineff= 2 , 0
          319.92 1468.78
Permanent Ineff=
       F       F
Bank Sta=449.88,465.1
XS Rating Curve= 0 ,0
Exp/Cntr=0.3,0.1

Type RM Length L Ch R = 1 ,14516.8 ,183.8,157.1,129.7
XS GIS Cut Line= 4
     1861561.158      264278.089     1861694.621       264526.57
     1861456.991       264841.24     1861548.137      264957.342
#Sta/Elev= 30
       0 1548.74    19.4 1542.14    48.6 1530.89    87.5 1519.53   116.7 1512.82
   165.3 1504.89   175.1 1502.28   184.8 1497.52   204.2 1485.15     214 1481.52
   243.2 1473.36  257.781470.215  265.231469.217   282.1 1467.98   310.61467.358
  344.761467.014   378.2 1465.88  420.88 1461.35   426.3  1460.9  437.841461.393
   464.8 1467.59   474.4  1467.6  490.961466.392  603.141465.235   637.9 1465.66
  694.291467.558   715.7 1468.72  731.221470.965   774.8  1475.9     824 1478.83
#Mann= 11 ,-1 , 0
       0     .12       0  257.78     .06       0  265.23     .12       0
   310.6     .06       0  344.76     .12       0  420.88    .045       0
  437.84     .12       0  490.96     .06       0  603.14     .12       0
  694.29    .016       0  731.22     .06       0
#XS Ineff= 2 , 0
           358.1 1468.61   619.2         1468.28
Permanent Ineff=
       F       F
Bank Sta=420.88,437.84
XS Rating Curve= 0 ,0
Exp/Cntr=0.3,0.1

Type RM Length L Ch R = 1 ,14359.7 ,380.2,390.8,401.2
XS GIS Cut Line= 4
     1861328.953      264362.724      1861516.67       264687.16
     1861412.503      264840.155      1861516.67      264969.278
#Sta/Elev= 30
       0    1568     9.6 1563.68    19.2  1558.1    38.4 1545.46      48 1539.76
    57.7 1535.18    76.9 1528.25    96.1 1523.59   134.6 1519.12     173 1512.17
   182.6 1508.95   192.2 1503.04   211.4 1490.19   240.3 1475.68   259.5 1465.35
  267.971462.156   278.7 1461.02  284.331462.087   297.9 1465.82   307.6  1467.3
  313.051467.504   374.8 1467.23  461.771464.857   530.7 1466.56   569.7  1466.9
  606.251468.099   628.2  1468.9  651.441471.319   686.8 1475.74   725.8 1478.36
#Mann= 7 ,-1 , 0
       0     .12       0  267.97    .045       0  284.33     .12       0
  313.05     .06       0  461.77     .12       0  606.25    .016       0
  651.44     .06       0
Bank Sta=267.97,284.33
XS Rating Curve= 0 ,0
Exp/Cntr=0.3,0.1

Type RM Length L Ch R = 1 ,13968.8 ,339,343.4,347.5
XS GIS Cut Line= 4
      1861165.05      264427.322     1861111.664      264681.228
     1861125.987      264918.207     1861086.925      265048.416
#Sta/Elev= 30
       0 1541.01     9.6 1537.58    28.8 1529.86    38.4 1527.08    57.7 1522.46
    67.3 1519.79    86.5 1514.01   134.5 1498.76   163.4 1490.84     173 1488.62
   182.6 1486.85   201.8 1484.54   259.5 1476.63   297.4 1470.84   306.9 1469.12
   316.4 1466.86   325.9 1463.88   335.4  1460.2  342.641458.003   344.9 1457.32
   354.4 1456.59   363.9 1458.02  375.971461.689   382.9 1463.87   392.4 1465.98
   401.9 1467.04   411.4 1467.48   477.9 1469.12   555.1 1469.54   632.8 1470.68
#Mann= 4 ,-1 , 0
       0     .12       0  342.64    .045       0   363.9     .12       0
  375.97     .06       0
Bank Sta=342.64,363.9
XS Rating Curve= 0 ,0
Exp/Cntr=0.3,0.1

Type RM Length L Ch R = 1 ,13625.5 ,158,157.1,156.3
XS GIS Cut Line= 3
     1860814.789      264441.645     1860767.914      264803.624
     1860862.966      265023.676
#Sta/Elev= 30
       0 1531.34     9.6 1527.78    19.2  1524.6    57.6 1513.84    76.8 1508.79
      96 1504.37   144.1 1494.23   163.3 1490.42   182.5 1486.01   211.3 1479.07
   230.5  1474.2   259.3  1466.2   288.2  1457.5   293.1 1456.76   297.8 1456.05
   307.4 1456.88     317 1460.32   326.6 1464.72   336.2 1468.45   345.8 1471.01
   355.4  1472.2   374.6 1471.81  380.071471.867   403.4  1472.4   422.5 1472.42
   460.9 1474.11   470.5 1474.18     528 1473.48   575.9 1472.46   604.7 1472.39
#Mann= 4 ,-1 , 0
       0     .12       0   293.1    .045       0   307.4     .12       0
  380.07     .06       0
Bank Sta=293.1,307.4
XS Rating Curve= 0 ,0
Exp/Cntr=0.3,0.1

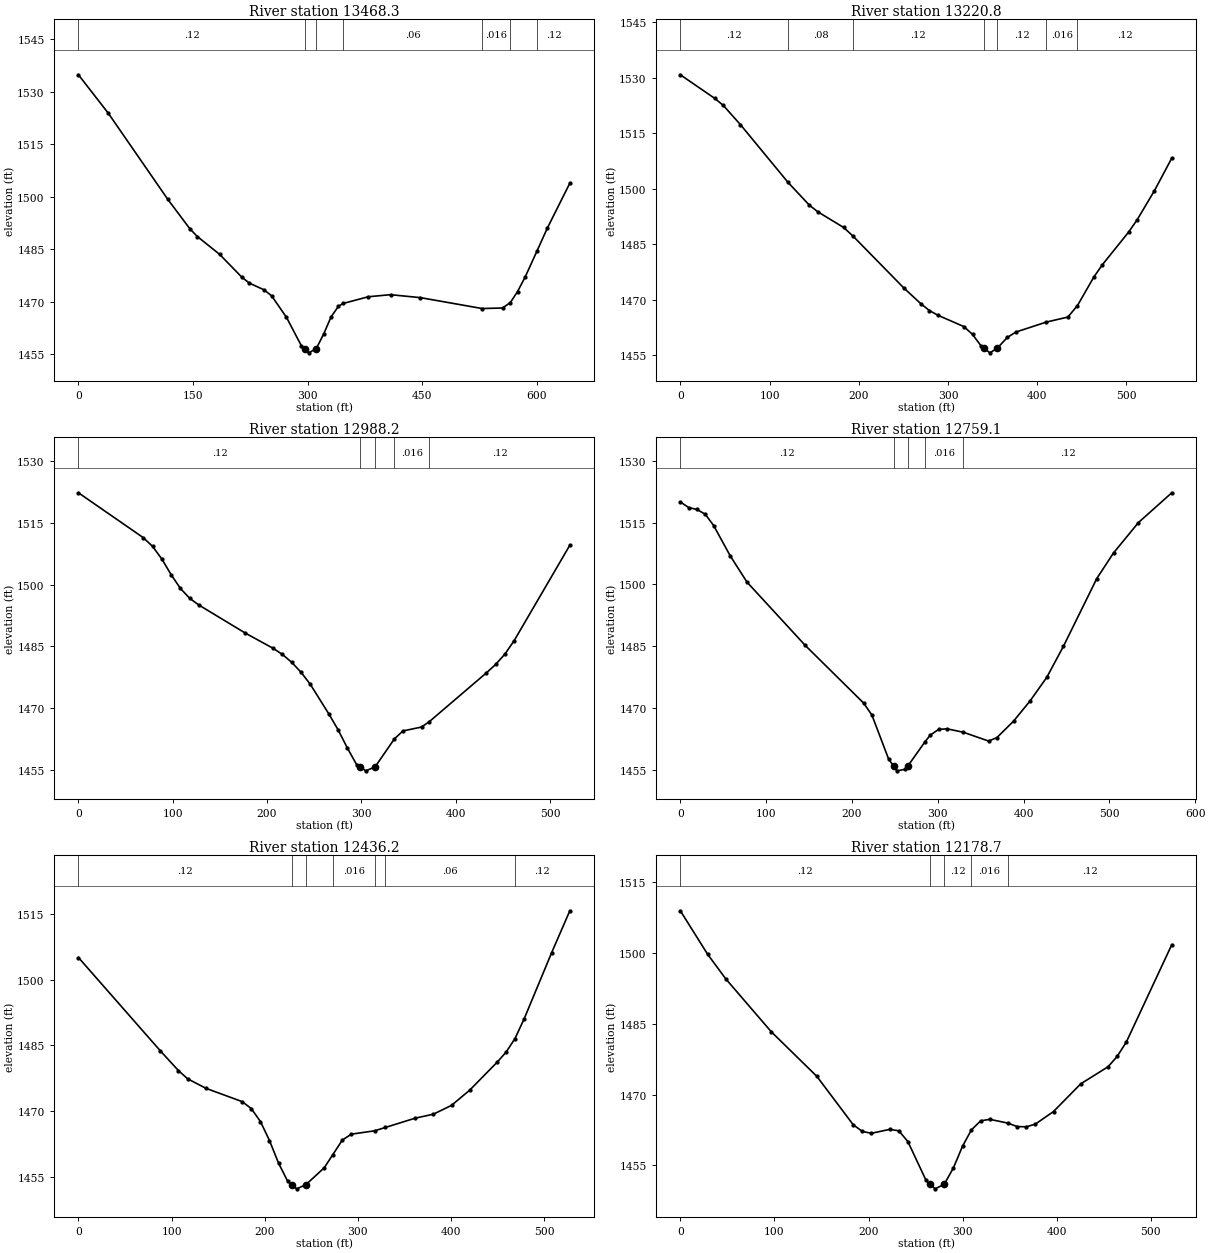
Type RM Length L Ch R = 1 ,13468.3 ,236,247.5,259.1
XS GIS Cut Line= 3
     1860646.821      264429.926      1860609.06      264846.593
     1860459.321      265014.561
#Sta/Elev= 30
       0 1534.88    38.9 1523.95   116.8 1499.32   145.9 1490.84   155.7 1488.62
   184.9 1483.52     214 1476.98   223.8  1475.3   243.2 1473.36     253 1471.65
   272.4 1465.51   291.9 1457.38     2961456.526   301.6 1455.36   311.4 1456.57
   321.1 1460.74   330.8 1465.65   340.5 1468.69  346.621469.483   379.5  1471.4
   408.6 1471.99   447.7 1471.15  528.481468.034   555.3 1468.18  565.551469.751
   574.9 1472.88   584.7 1476.96  600.631484.586     614 1491.06   643.4 1503.88
#Mann= 7 ,-1 , 0
       0     .12       0     296    .045       0   311.4     .12       0
  346.62     .06       0  528.48    .016       0  565.55     .06       0
  600.63     .12       0
Bank Sta=296,311.4
XS Rating Curve= 0 ,0
Exp/Cntr=0.3,0.1

Type RM Length L Ch R = 1 ,13220.8 ,231.2,232.6,233.3
XS GIS Cut Line= 3
     1860471.907      264395.204     1860395.518      264693.815
     1860260.102      264895.204
#Sta/Elev= 30
       0 1530.84    38.5 1524.46    48.2 1522.54    67.4 1517.34  120.751501.713
   144.5 1495.59   154.1 1493.76     183 1489.53   193.31487.255   250.4 1473.18
   269.7 1468.87   279.3 1467.03     289 1465.74   317.9  1462.7   327.6 1460.57
   337.4 1457.38  340.021456.897   347.1  1455.6  355.471456.902   366.5 1459.76
   376.2 1461.23  410.08 1463.91   434.4 1465.28  445.161468.381   463.5  1476.1
   473.2 1479.47   502.4 1488.24   512.1  1491.6   531.5 1499.49   550.9 1508.28
#Mann= 7 ,-1 , 0
       0     .12       0  120.75     .08       0   193.3     .12       0
  340.02    .045       0  355.47     .12       0  410.08    .016       0
  445.16     .12       0
Bank Sta=340.02,355.47
XS Rating Curve= 0 ,0
Exp/Cntr=0.3,0.1

Type RM Length L Ch R = 1 ,12988.2 ,228.5,229.1,229.7
XS GIS Cut Line= 2
     1860361.664      264364.822     1860050.466      264782.791
#Sta/Elev= 30
       0 1522.31    68.8  1511.4    78.7 1509.27    88.5  1506.2    98.3 1502.41
   108.2 1499.06     118 1496.67   127.8 1495.03     177 1488.22   206.5 1484.52
   216.3 1483.04   226.1 1481.14     236 1478.72   245.8 1475.81   265.5  1468.6
   275.3 1464.75   285.1 1460.34     295 1456.27  299.081455.642   304.8 1454.76
   314.6 1455.73  335.071462.524   344.1 1464.45   363.8  1465.4   371.91466.673
   432.6 1478.56   442.4  1480.6   452.3 1483.13   462.1 1486.41   521.1 1509.57
#Mann= 5 ,-1 , 0
       0     .12       0  299.08    .045       0   314.6     .08       0
  335.07    .016       0   371.9     .12       0
Bank Sta=299.08,314.6
XS Rating Curve= 0 ,0
Exp/Cntr=0.3,0.1

Type RM Length L Ch R = 1 ,12759.1 ,323.1,323,322.7
XS GIS Cut Line= 2
     1860163.797      264259.321     1859809.917      264709.766
#Sta/Elev= 30
       0 1520.02     9.7 1518.65    19.4 1518.19    29.1 1517.02    38.8 1514.29
    58.2 1506.91    77.7 1500.56   145.6  1485.2   213.6 1471.22   223.3  1468.3
   242.7 1457.66  248.841455.831   252.4 1454.77   262.1 1455.15  264.861455.857
  285.421461.888   291.3 1463.44     301 1464.81   310.7 1464.97  329.92 1464.13
   359.2    1462   368.9 1462.82   388.4 1466.83   407.8 1471.78   427.2 1477.49
   446.6 1485.02   485.4 1501.43   504.9 1507.64     534 1515.02   572.8 1522.24
#Mann= 5 ,-1 , 0
       0     .12       0  248.84    .045       0  264.86     .12       0
  285.42    .016       0  329.92     .12       0
Bank Sta=248.84,264.86
XS Rating Curve= 0 ,0
Exp/Cntr=0.3,0.1

Type RM Length L Ch R = 1 ,12436.2 ,254.7,257.4,260.1
XS GIS Cut Line= 2
     1859904.253      264064.232     1859582.234      264482.032
#Sta/Elev= 30
       0 1505.05    87.9 1483.75   107.4 1479.22   117.2 1477.36   136.8 1475.19
   175.8 1472.14   185.6 1470.54   195.4 1467.59   205.1 1463.25   214.9 1458.06
   224.7 1453.93  228.881453.196   234.4 1452.23   244.2 1453.19   263.8 1457.02
  272.821459.958   283.3 1463.38     293 1464.71  318.051465.489  329.521466.248
   361.4 1468.36     381 1469.27   400.5 1471.29     420 1474.76   449.4 1481.13
   459.1 1483.45  468.641486.555   478.6 1491.12     508 1506.17   527.5 1515.72
#Mann= 7 ,-1 , 0
       0     .12       0  228.88    .045       0   244.2     .12       0
  272.82    .016       0  318.05     .12       0  329.52     .06       0
  468.64     .12       0
Bank Sta=228.88,244.2
XS Rating Curve= 0 ,0
Exp/Cntr=0.3,0.1

Type RM Length L Ch R = 1 ,12178.7 ,317.8,319.6,321.9
XS GIS Cut Line= 2
     1859746.724      263901.844      1859380.25      264274.045
#Sta/Elev= 30
       0 1508.96      29 1499.74    48.4  1494.5    96.7 1483.31   145.1 1473.87
   183.8  1463.6   193.5  1462.2   203.1 1461.81   222.5 1462.64   232.2 1462.34
   241.8 1460.06   261.2 1451.81   265.2 1451.07   270.8 1450.04   280.5 1451.01
   290.2 1454.47   299.9 1459.07  309.341462.531   319.2 1464.45   328.9 1464.77
   347.91463.977   357.9 1463.24   367.6 1463.18   377.2 1463.74   396.6 1466.42
   425.6  1472.3   454.6 1475.91   464.3 1478.11     474 1481.14   522.3 1501.77
#Mann= 5 ,-1 , 0
       0     .12       0   265.2    .045       0   280.5     .12       0
  309.34    .016       0   347.9     .12       0
Bank Sta=265.2,280.5
XS Rating Curve= 0 ,0
Exp/Cntr=0.3,0.1

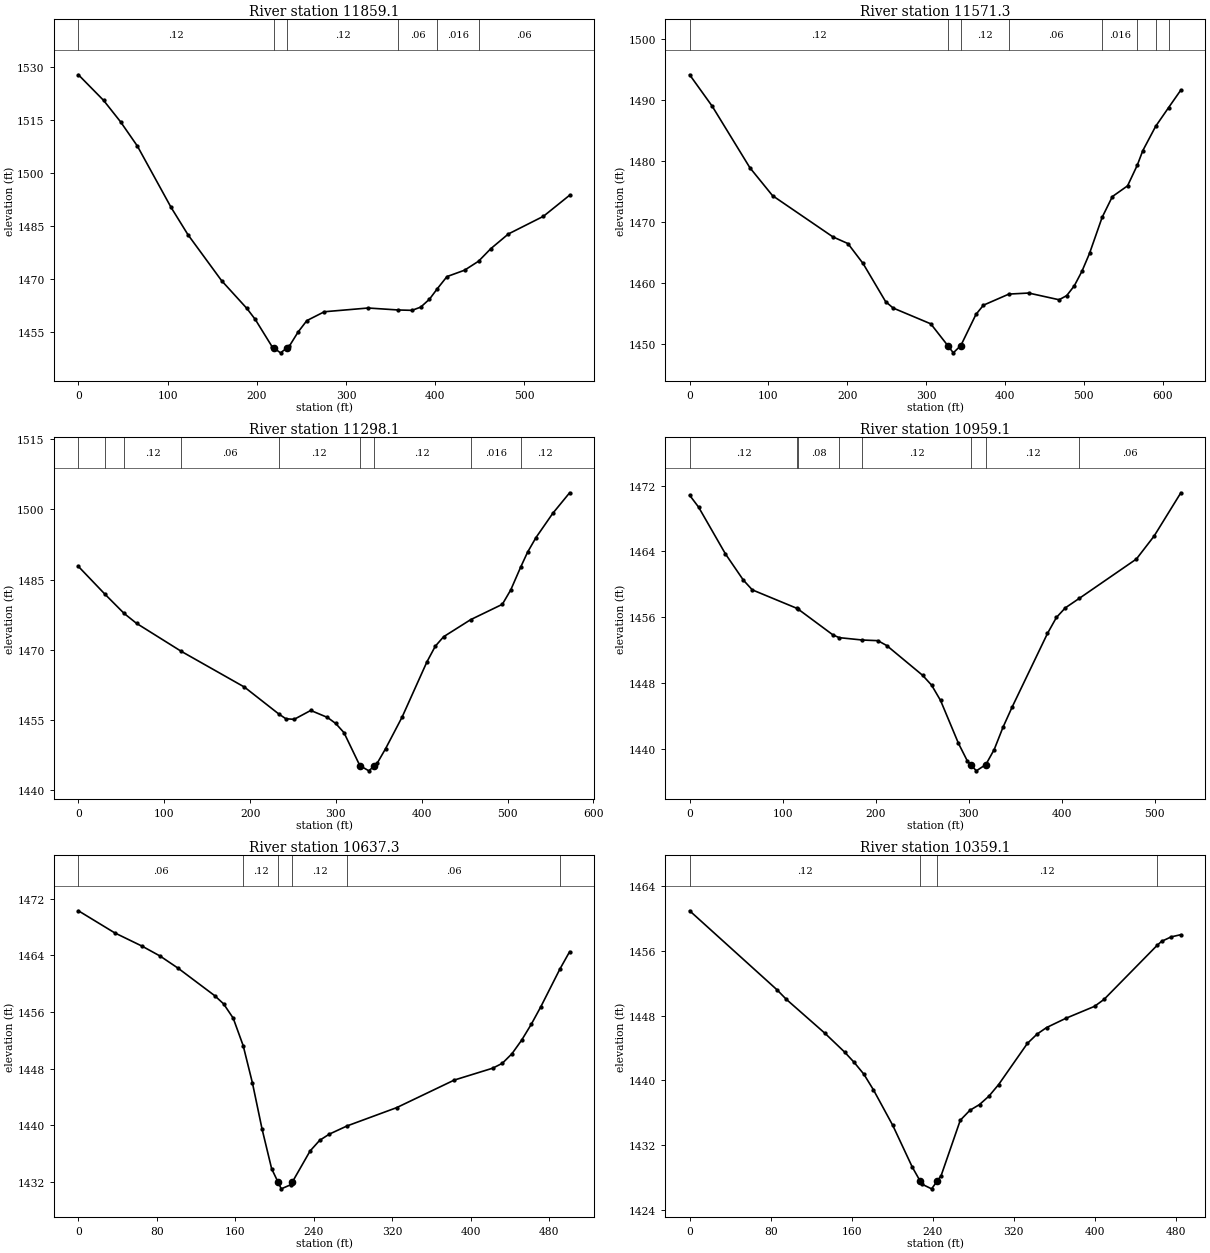
Type RM Length L Ch R = 1 ,11859.1 ,310.7,287.8,263.4
XS GIS Cut Line= 3
     1859604.755      263665.482     1859435.135      263815.784
     1859183.377      264019.878
#Sta/Elev= 30
       0 1527.88    28.3  1520.6    47.2 1514.56    66.1 1507.67   103.9 1490.27
   122.8 1482.54   160.5 1469.51   188.9 1461.62   198.3  1458.5   217.2 1450.76
   219.1 1450.41   226.6 1449.04   234.1 1450.48   236.4 1450.92   246.3 1454.95
   256.1 1458.18   275.7 1460.69   324.8 1461.75  358.72 1461.19     374 1461.09
   383.8 1462.01   393.6 1464.26  402.371467.222   413.2 1470.66   432.9 1472.47
   448.61475.018   462.3 1478.57     482 1482.74   521.3 1487.75   550.7 1493.73
#Mann= 6 ,-1 , 0
       0     .12       0   219.1    .045       0   234.1     .12       0
  358.72     .06       0  402.37    .016       0   448.6     .06       0
Bank Sta=219.1,234.1
XS Rating Curve= 0 ,0
Exp/Cntr=0.3,0.1

Type RM Length L Ch R = 1 ,11571.3 ,245,273.2,301.3
XS GIS Cut Line= 4
     1859361.664      263427.322     1859201.508      263513.259
     1859239.268      263748.936     1859089.529      263885.655
#Sta/Elev= 30
       0 1494.07    28.7 1488.91    76.5 1478.84   105.2 1474.28   181.8 1467.53
   200.8 1466.44     220 1463.18   248.6 1456.94   258.1 1455.89   305.9  1453.3
  327.921449.668   334.5 1448.55   344.1 1449.75   363.2 1454.83   372.7 1456.35
  405.051458.168   430.1 1458.34   468.7 1457.24   478.4 1457.92     488 1459.52
   497.7  1461.9   507.3 1464.82  523.32 1470.73   536.3 1474.13   555.6 1475.89
  567.991479.289   574.9 1481.65  591.171485.619  607.631488.697   623.2 1491.57
#Mann= 8 ,-1 , 0
       0     .12       0  327.92    .045       0   344.1     .12       0
  405.05     .06       0  523.32    .016       0  567.99     .06       0
  591.17     .12       0  607.63     .06       0
Bank Sta=327.92,344.1
XS Rating Curve= 0 ,0
Exp/Cntr=0.3,0.1

Type RM Length L Ch R = 1 ,11298.1 ,346.3,339,335.2
XS GIS Cut Line= 3
     1859295.258      263373.936     1858911.143      263578.364
     1858812.185      263673.416
#Sta/Elev= 30
       0  1487.8   30.711481.906   53.271477.748    67.7 1475.63  119.891469.637
   193.4    1462  233.451456.243   241.7 1455.22   251.4  1455.1   270.7    1457
   290.1 1455.51   299.8 1454.21   309.4 1452.25  327.871445.207   338.4 1444.08
  343.981445.019   348.1 1445.71   357.8  1448.8   377.1 1455.57   406.1 1467.41
   415.8 1470.74   425.5 1472.77  456.971476.417   493.9  1479.7   503.7 1482.78
  515.081487.579   523.3 1490.85   533.1 1493.98   552.7 1499.17   572.3 1503.56
#Mann= 9 ,-1 , 0
       0     .12       0   30.71     .08       0   53.27     .12       0
  119.89     .06       0  233.45     .12       0  327.87    .045       0
  343.98     .12       0  456.97    .016       0  515.08     .12       0
Bank Sta=327.87,343.98
XS Rating Curve= 0 ,0
Exp/Cntr=0.3,0.1

Type RM Length L Ch R = 1 ,10959.1 ,324.8,321.8,315
XS GIS Cut Line= 3
     1859048.475      263028.346     1858850.363       263264.62
      1858686.62      263411.322
#Sta/Elev= 30
       0 1470.82     9.6 1469.38    38.5 1463.69    57.8  1460.5    67.4 1459.32
  115.741457.059  116.031457.035   154.2 1453.84  160.821453.516  185.771453.226
   202.4 1453.15     212 1452.55   250.5 1448.94   260.2 1447.74   269.8 1445.88
   289.1 1440.66   298.7 1438.51  302.311438.065   308.3 1437.33  318.511438.094
   327.5 1439.92     337 1442.64   346.6 1445.04   384.8 1454.03   394.4 1455.97
   403.9 1457.13  419.051458.293   480.4 1463.07   499.5 1465.87   528.2 1471.12
#Mann= 8 ,-1 , 0
       0     .12       0  115.74     .06       0  116.03     .08       0
  160.82     .06       0  185.77     .12       0  302.31    .045       0
  318.51     .12       0  419.05     .06       0
Bank Sta=302.31,318.51
XS Rating Curve= 0 ,0
Exp/Cntr=0.3,0.1

Type RM Length L Ch R = 1 ,10637.3 ,284,278.2,273.1
XS GIS Cut Line= 3
     1858806.977      262898.676     1858684.252      262981.406
      1858478.44      263267.985
#Sta/Elev= 30
       0  1470.3      37 1467.18    64.8 1465.31    83.2 1463.91   101.8 1462.17
   138.8 1458.32     148 1457.15   157.8 1455.13  168.011451.231   177.4 1445.98
   187.2 1439.48     197 1433.85  203.351432.009   206.8 1431.01   216.6  1431.6
  218.151431.986   236.2 1436.36     246 1437.87   255.8 1438.74  273.991439.904
   324.4 1442.48   383.2 1446.38   422.4 1448.06   432.2 1448.75     442  1450.1
   451.8    1452   461.6 1454.24   471.4 1456.73  490.82 1462.05   500.8 1464.52
#Mann= 6 ,-1 , 0
       0     .06       0  168.01     .12       0  203.35    .045       0
  218.15     .12       0  273.99     .06       0  490.82    .016       0
Bank Sta=203.35,218.15
XS Rating Curve= 0 ,0
Exp/Cntr=0.3,0.1

Type RM Length L Ch R = 1 ,10359.1 ,299.4,303.9,307.5
XS GIS Cut Line= 3
     1858477.205      262699.739     1858392.482      262923.068
     1858297.136      263149.944
#Sta/Elev= 30
       0 1460.93      86 1451.21    95.5    1450   133.8 1445.79   152.9 1443.51
   162.4 1442.23     172 1440.77   181.5 1438.83   200.6 1434.44   219.8 1429.31
   227.41427.622   229.3  1427.2   238.9 1426.62  244.641427.615   248.3 1428.25
   267.2 1435.08   276.7 1436.31   286.2 1437.02   295.6 1438.07   305.1 1439.49
   333.5 1444.57     343 1445.71   352.4 1446.52   371.4 1447.66   399.8 1449.14
   409.2    1450  461.591456.667     466 1457.16   475.5 1457.71     485 1457.98
#Mann= 4 ,-1 , 0
       0     .12       0   227.4    .045       0  244.64     .12       0
  461.59    .016       0
Bank Sta=227.4,244.64
XS Rating Curve= 0 ,0
Exp/Cntr=0.3,0.1