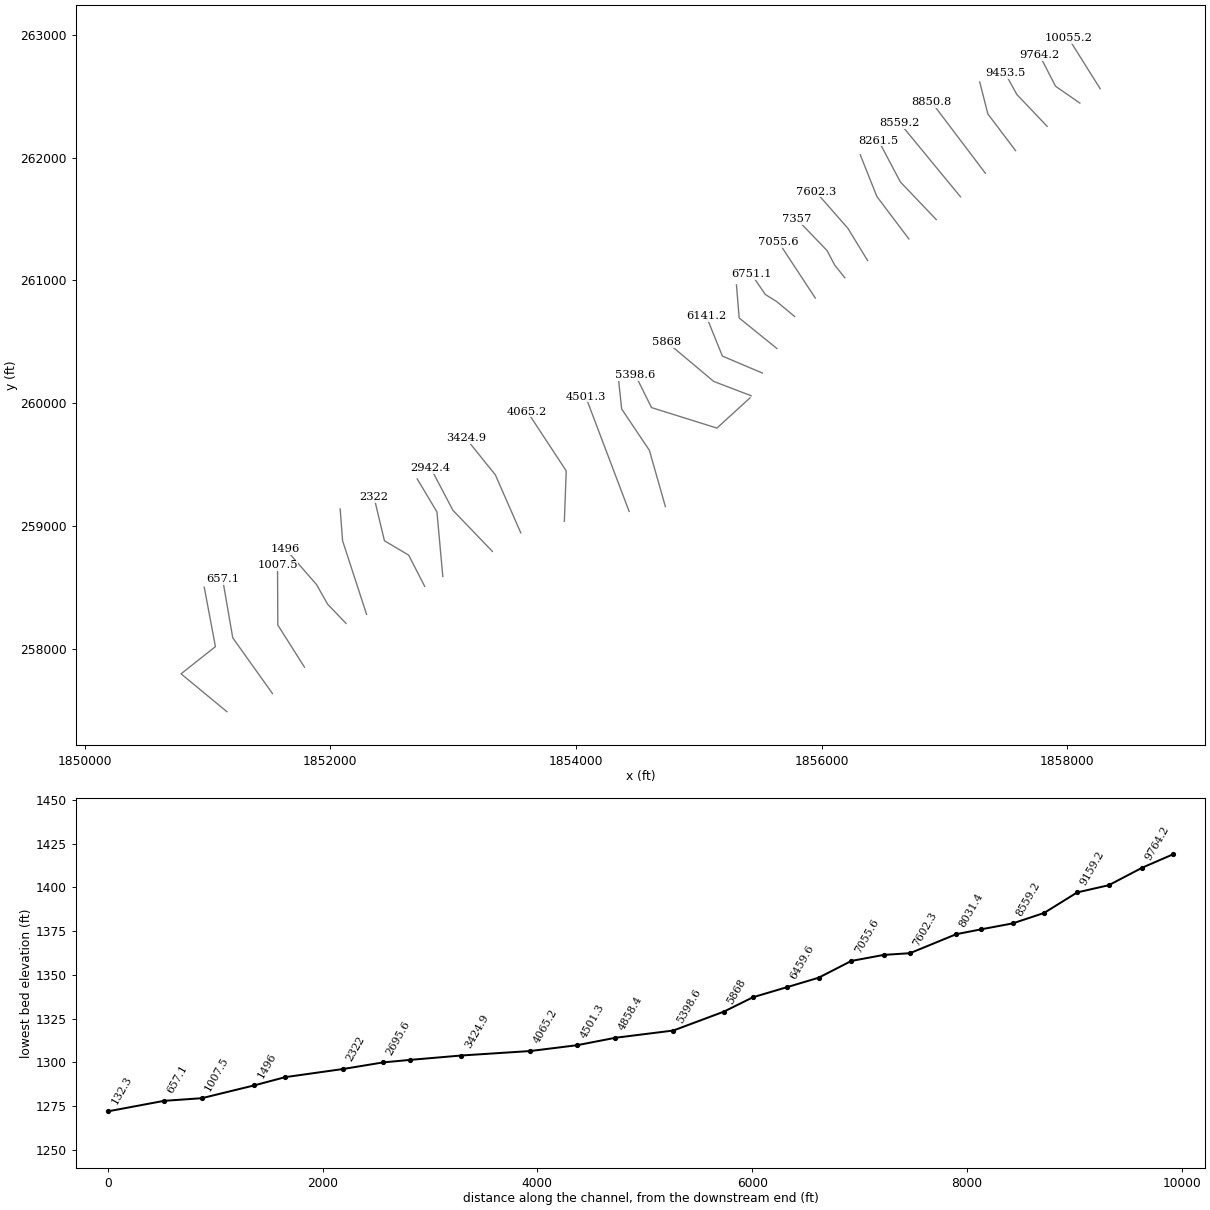
HEC-RAS study RACCOONRN.prj: RACCOONRN

--- RACCOONRN.g01 (geometry) --- (continued)

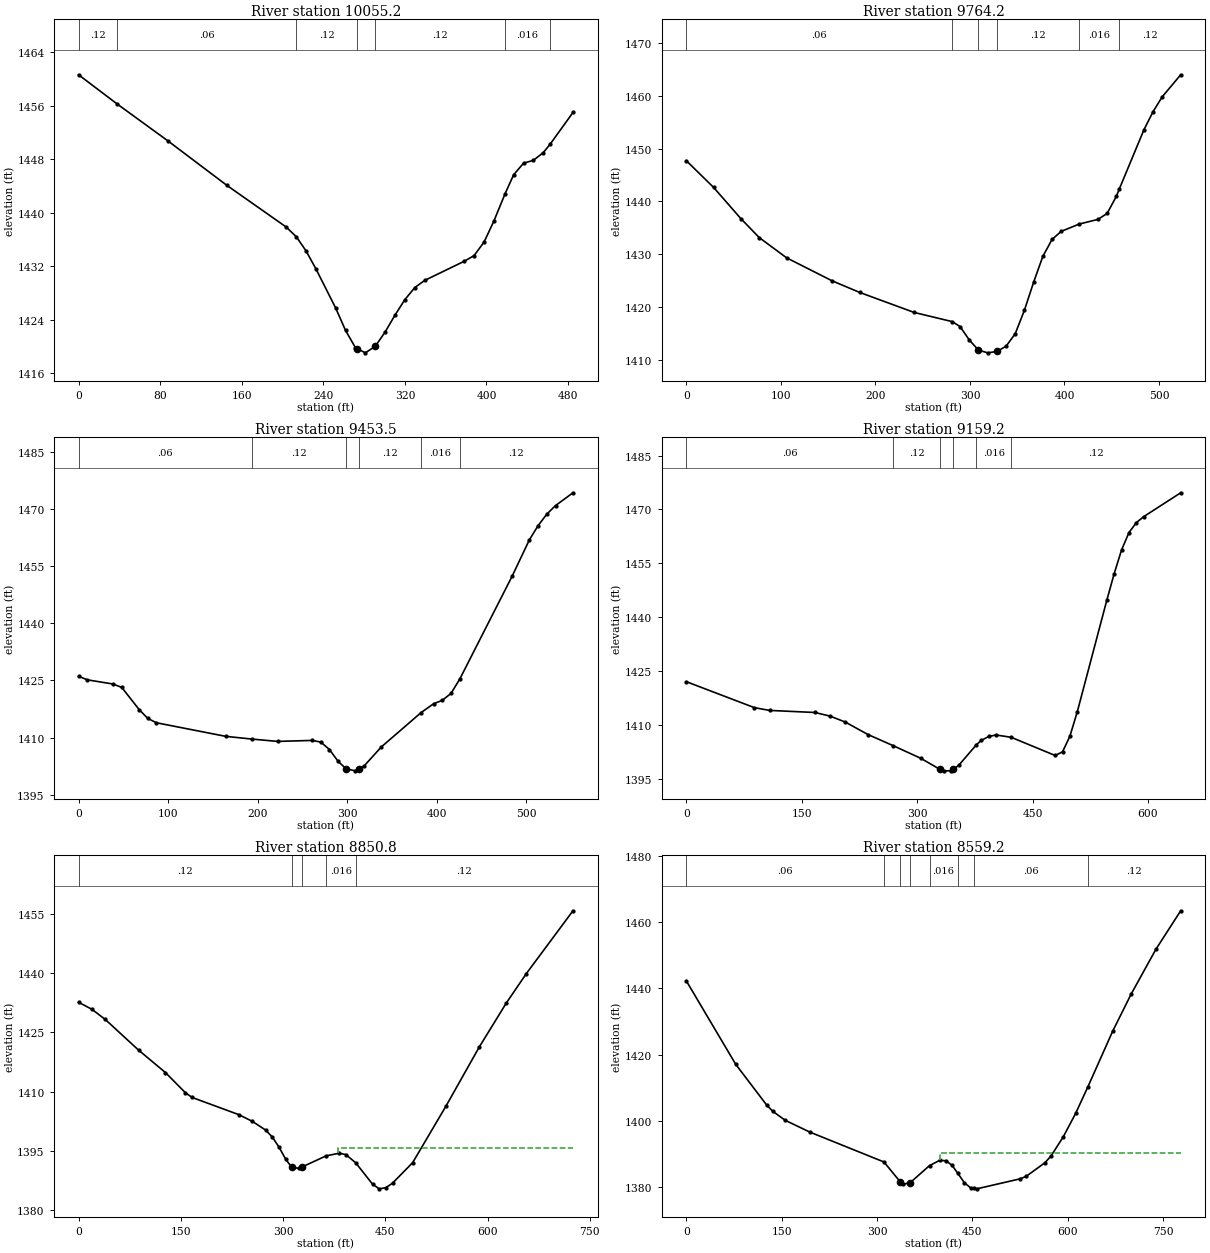
Type RM Length L Ch R = 1 ,10055.2 ,293,291.1,289.2
XS GIS Cut Line= 2
     1858266.705      262559.912     1858008.901      262970.498
#Sta/Elev= 30
       0 1460.64   38.121456.237    87.3 1450.78   145.4 1444.09   203.6 1437.85
  213.641436.374     223 1434.29   232.7  1431.6   252.1 1425.73   261.8 1422.37
   271.5 1419.79   273.41419.639   281.2 1419.02   290.9 1419.99   300.6 1422.14
   310.3 1424.67     320 1426.99   329.7 1428.79   339.4 1429.86   378.2 1432.73
   387.8 1433.57   397.6  1435.6   407.2 1438.73  418.151442.804   426.6 1445.67
   436.3  1447.4     446 1447.84   455.7 1448.99  462.271450.223   484.8    1455
#Mann= 7 ,-1 , 0
       0     .12       0   38.12     .06       0  213.64     .12       0
   273.4    .045       0   290.9     .12       0  418.15    .016       0
  462.27     .12       0
Bank Sta=273.4,290.9
XS Rating Curve= 0 ,0
Exp/Cntr=0.3,0.1

Type RM Length L Ch R = 1 ,9764.2  ,304,310.6,317
XS GIS Cut Line= 3
     1858101.248      262442.947      1857903.19      262580.263
     1857774.236      262830.913
#Sta/Elev= 30
       0 1447.73    28.9 1442.65    57.8 1436.72    77.1 1433.15     106 1429.31
   154.2 1424.94   183.2 1422.75     241 1418.94  281.31  1417.2   289.6 1416.26
   299.3 1413.71     309  1411.8   318.8 1411.28   328.5 1411.54   338.2 1412.53
   347.9 1414.91   357.6 1419.35   367.4  1424.7   377.1 1429.58   386.8 1432.78
   396.5 1434.32  415.761435.714   435.4 1436.59   445.1 1437.72   454.8 1440.95
  458.071442.405     484 1453.58   493.7 1457.04   503.4 1459.85   522.9 1464.02
#Mann= 6 ,-1 , 0
       0     .06       0  281.31     .12       0     309    .045       0
   328.5     .12       0  415.76    .016       0  458.07     .12       0
Bank Sta=309,328.5
XS Rating Curve= 0 ,0
Exp/Cntr=0.3,0.1

Type RM Length L Ch R = 1 ,9453.5  ,296.8,294.4,291.7
XS GIS Cut Line= 3
     1857834.585      262254.112     1857588.227      262513.259
     1857494.477      262683.832
#Sta/Elev= 30
       0 1426.11     9.7 1425.17    38.7 1424.06    48.3 1423.16    67.6 1417.38
    77.3 1415.03      87  1413.9   164.3 1410.34  193.171409.634   222.3 1409.01
   260.9 1409.27   270.6 1408.83   280.2 1406.88   289.9 1403.78  298.721401.834
   309.2 1401.29  312.861401.774   318.9 1402.57   338.2 1407.57  382.551416.572
   396.5 1418.89   406.2 1419.78     416 1421.61  425.751425.363   484.1 1452.29
   503.5 1461.89   513.3 1465.64     523 1468.64   532.7 1470.88   552.2 1474.24
#Mann= 6 ,-1 , 0
       0     .06       0  193.17     .12       0  298.72    .045       0
  312.86     .12       0  382.55    .016       0  425.75     .12       0
Bank Sta=298.72,312.86
XS Rating Curve= 0 ,0
Exp/Cntr=0.3,0.1

Type RM Length L Ch R = 1 ,9159.2  ,308.3,308.3,308.3
XS GIS Cut Line= 3
     1857577.865      262056.149      1857352.55      262354.405
     1857286.143      262614.822
#Sta/Elev= 30
       0 1422.01    88.5 1414.77   108.2    1414   167.2 1413.42   186.9 1412.41
   206.6 1410.76   236.1 1407.28  269.211404.145   304.9 1400.64  329.131397.637
   334.4 1397.16   344.3 1397.16  346.87 1397.56   354.1 1398.69  377.071404.436
   383.4 1405.63     393 1406.73   402.6 1407.15  422.161406.514   479.4 1401.44
     489 1402.45   498.6 1406.82   508.2 1413.62   546.6 1444.73   556.2 1452.15
   565.8 1458.75   575.4 1463.57     585 1466.34   594.6 1468.01   642.6 1474.65
#Mann= 6 ,-1 , 0
       0     .06       0  269.21     .12       0  329.13    .045       0
  346.87     .12       0  377.07    .016       0  422.16     .12       0
Bank Sta=329.13,346.87
XS Rating Curve= 0 ,0
Exp/Cntr=0.3,0.1

Type RM Length L Ch R = 1 ,8850.8  ,290.6,291.6,292.4
XS GIS Cut Line= 2
     1857332.203      261871.902     1856894.679      262450.252
#Sta/Elev= 30
       0 1432.57    19.6 1430.79    39.2 1428.22    88.2 1420.45   127.4 1414.81
   156.8 1409.69   166.6 1408.51   235.2 1404.16   254.8 1402.48   274.4 1400.27
   284.2 1398.51     294 1395.96   303.8 1392.92   312.6 1390.87   323.4  1390.6
   327.6 1390.93  363.291393.767   382.2 1394.41     392 1394.08  406.421392.021
   431.2  1386.6     441 1385.42   450.8 1385.71   460.6 1386.87     490 1392.03
     539 1406.35     588 1421.34   627.2 1432.32   656.6 1439.77   725.2 1455.69
#Mann= 5 ,-1 , 0
       0     .12       0   312.6    .045       0   327.6     .12       0
  363.29    .016       0  406.42     .12       0
#XS Ineff= 2 , 0
                           380.6         1395.81
Permanent Ineff=
       F       F
Bank Sta=312.6,327.6
XS Rating Curve= 0 ,0
Exp/Cntr=0.3,0.1

Type RM Length L Ch R = 1 ,8559.2  ,296.1,297.7,299.4
XS GIS Cut Line= 2
     1857129.656      261680.199     1856635.301        262280.7
#Sta/Elev= 30
       0 1442.23    77.8 1417.03   126.4 1404.77   136.1 1402.86   155.6 1400.15
   194.4 1396.59  311.021387.569   336.8 1381.53   340.3 1380.86   351.8 1381.26
  382.671386.482   398.6 1388.06   408.4 1387.95   418.1 1386.57  426.691384.276
   437.5 1381.31   447.2 1379.78  453.291379.587     457 1379.47     525 1382.48
   534.7 1383.24   563.9  1387.3   573.6 1389.32   593.1 1395.17   612.5 1402.23
  631.93 1410.31   670.9 1427.08     700 1438.29   738.9 1451.79   777.8 1463.37
#Mann= 8 ,-1 , 0
       0     .06       0  311.02     .12       0   336.8    .045       0
   351.8     .12       0  382.67    .016       0  426.69     .12       0
  453.29     .06       0  631.93     .12       0
#XS Ineff= 2 , 0
                          398.76          1390.2
Permanent Ineff=
       F       F
Bank Sta=336.8,351.8
XS Rating Curve= 0 ,0
Exp/Cntr=0.3,0.1

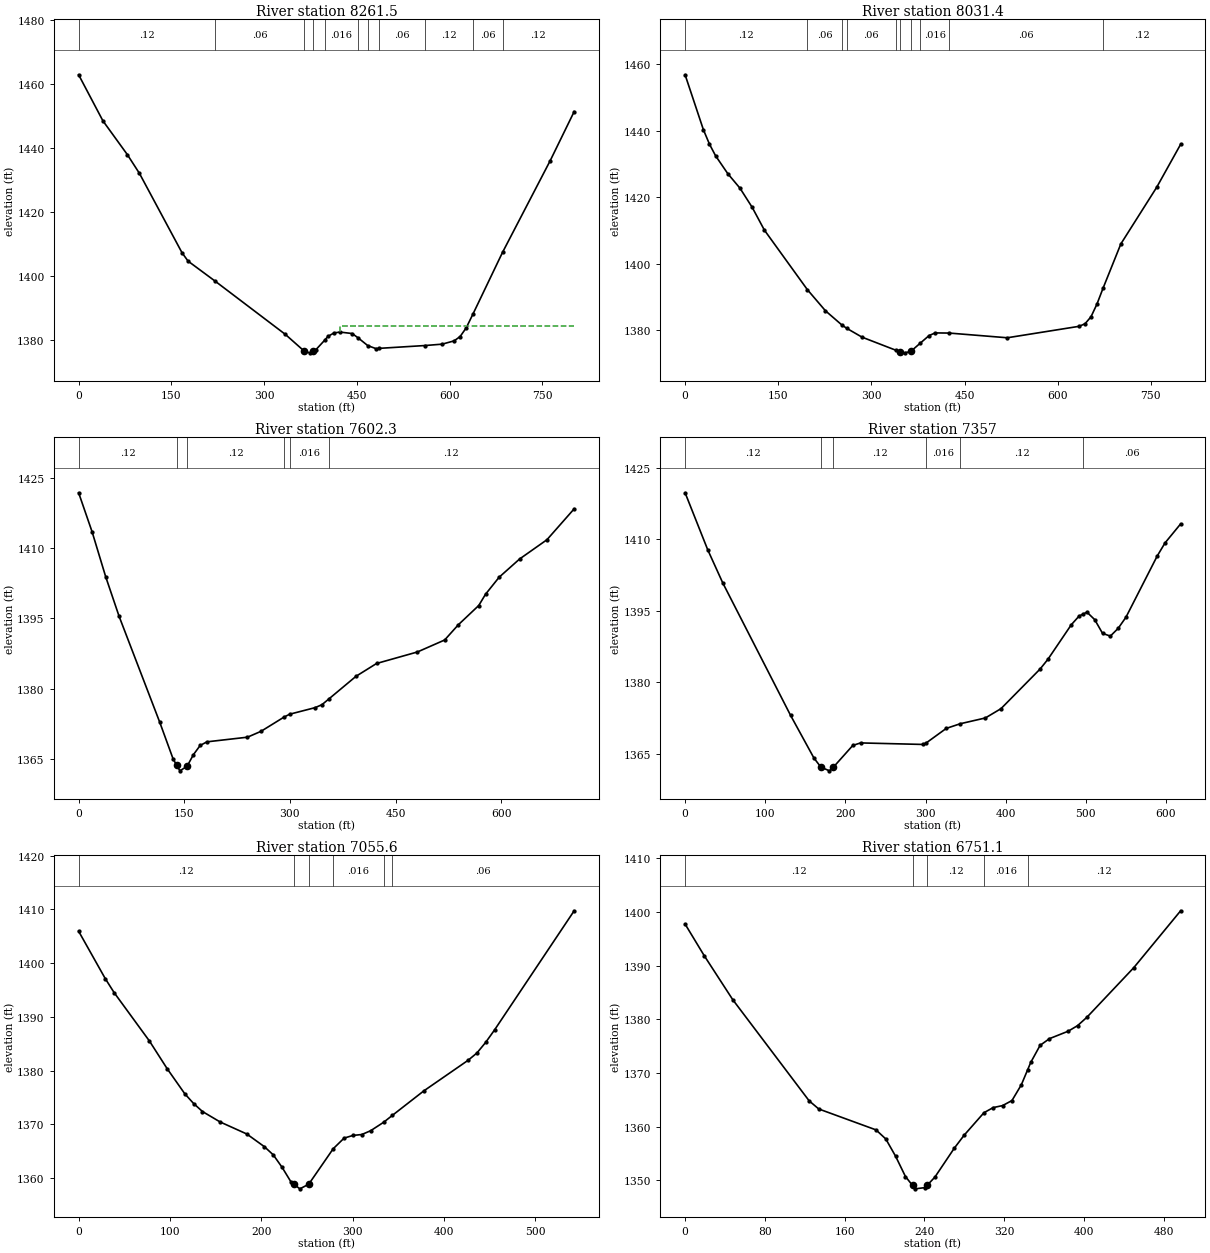
Type RM Length L Ch R = 1 ,8261.5  ,232.7,230.1,227.5
XS GIS Cut Line= 3
     1856932.208      261495.086      1856640.31       261801.02
     1856463.227      262135.655
#Sta/Elev= 30
       0 1462.85    39.3 1448.46    78.7 1437.95    98.3 1432.08   167.2 1407.29
     177 1404.67  220.16 1398.51   334.3  1381.8   364.7  1376.6   373.7 1376.04
   379.7 1376.62   383.5 1376.98   398.1 1380.02   403.2 1381.17     413 1382.26
   422.8 1382.52   442.3 1382.07  452.191380.687  467.671378.285   481.1 1377.34
  485.911377.439  560.621378.326   587.9 1378.75   607.3 1379.78     617 1381.14
   626.7 1383.81  637.741388.155  685.621407.437   762.6 1436.02   801.4 1451.36
#Mann= 11 ,-1 , 0
       0     .12       0  220.16     .06       0   364.7    .045       0
   379.7     .12       0   398.1    .016       0  452.19     .06       0
  467.67     .12       0  485.91     .06       0  560.62     .12       0
  637.74     .06       0  685.62     .12       0
#XS Ineff= 2 , 0
                          423.12         1384.53
Permanent Ineff=
       F       F
Bank Sta=364.7,379.7
XS Rating Curve= 0 ,0
Exp/Cntr=0.3,0.1

Type RM Length L Ch R = 1 ,8031.4  ,431.2,429.1,426.3
XS GIS Cut Line= 3
     1856709.321      261337.478     1856448.904       261682.53
     1856313.487      262022.374
#Sta/Elev= 30
       0 1456.84    29.5 1440.31    39.3 1435.97    49.1 1432.49    68.8 1427.11
    88.4 1422.75   108.1 1416.98   127.7 1410.15  196.841392.273     226 1385.91
  252.681381.601  260.481380.614   284.9 1377.98  339.541374.035  346.461373.585
   353.7 1373.26   363.5 1373.69  378.57 1376.14     393 1378.46   402.8 1379.25
  425.481379.202   518.9 1377.79   634.5 1381.23   644.1    1382   653.7 1384.09
   663.3  1387.9  673.04 1392.64   701.8    1406   759.6 1423.04   798.1 1435.94
#Mann= 10 ,-1 , 0
       0     .12       0  196.84     .06       0  252.68     .12       0
  260.48     .06       0  339.54     .12       0  346.46    .045       0
   363.5     .12       0  378.57    .016       0  425.48     .06       0
  673.04     .12       0
Bank Sta=346.46,363.5
XS Rating Curve= 0 ,0
Exp/Cntr=0.3,0.1

Type RM Length L Ch R = 1 ,7602.3  ,246.6,245.3,243.8
XS GIS Cut Line= 3
     1856373.383      261161.697     1856213.227      261423.416
     1855951.508      261721.593
#Sta/Elev= 30
       0 1421.86    19.2 1413.48    38.4 1403.93    57.5 1395.44   115.1 1372.85
   134.2 1364.96     139  1363.7   143.8 1362.44     154 1363.42     163  1365.9
   172.6 1367.87   182.2 1368.64   239.7 1369.63   258.9 1370.88     2921373.958
  299.661374.541   335.9 1375.95   345.5 1376.58  354.951377.759   393.9 1382.65
     423 1385.38     481 1387.84   519.7  1390.4   539.1 1393.65   568.1 1397.77
   577.8 1400.19   597.1 1403.82   626.2 1407.72   664.9 1411.82   703.6 1418.43
#Mann= 6 ,-1 , 0
       0     .12       0     139    .045       0     154     .12       0
     292     .06       0  299.66    .016       0  354.95     .12       0
Bank Sta=139,154
XS Rating Curve= 0 ,0
Exp/Cntr=0.3,0.1

Type RM Length L Ch R = 1 ,7357    ,299.3,301.4,303.4
XS GIS Cut Line= 4
     1856188.487      261021.072     1856106.122       261123.76
     1856042.654      261243.728     1855799.164      261496.332
#Sta/Elev= 30
       0 1419.71    28.2 1407.78      47 1400.82   131.6 1373.07   160.7 1364.14
  169.371362.235   180.1 1361.45  184.751362.173   209.2 1366.77   218.9  1367.3
   296.6 1366.98  300.581367.271   325.8 1370.34  343.191371.314   374.6 1372.53
   394.1 1374.48   442.8 1382.77   452.5 1384.79   481.8 1392.06   491.5 1393.88
  496.431394.292   501.3  1394.7     511 1393.13   520.8 1390.25   530.5 1389.68
   540.2 1391.29     550 1393.64     589 1406.47   598.7  1409.2   618.2 1413.19
#Mann= 6 ,-1 , 0
       0     .12       0  169.37    .045       0  184.75     .12       0
  300.58    .016       0  343.19     .12       0  496.43     .06       0
Bank Sta=169.37,184.75
XS Rating Curve= 0 ,0
Exp/Cntr=0.3,0.1

Type RM Length L Ch R = 1 ,7055.6  ,294.7,304.5,314.2
XS GIS Cut Line= 2
     1855947.458      260856.678     1855649.338      261309.946
#Sta/Elev= 30
       0 1405.95    29.1 1397.15    38.8 1394.54    77.5 1385.52    96.9 1380.37
   116.2  1375.7   125.9 1373.88   135.6 1372.39     155 1370.44   184.1 1368.21
   203.4 1365.84   213.1 1364.32   222.8 1361.99   232.5 1359.28  235.751358.851
   242.2    1358   251.9 1358.86  278.721365.468   290.6 1367.44   300.3 1367.94
     310 1368.11   319.7 1368.82  333.911370.391  343.311371.656   377.8 1376.22
   426.3 1381.92     436 1383.28   445.6 1385.26   455.3 1387.57   542.5 1409.76
#Mann= 6 ,-1 , 0
       0     .12       0  235.75    .045       0   251.9     .12       0
  278.72    .016       0  333.91     .12       0  343.31     .06       0
Bank Sta=235.75,251.9
XS Rating Curve= 0 ,0
Exp/Cntr=0.3,0.1

Type RM Length L Ch R = 1 ,6751.1  ,294.2,291.5,288.7
XS GIS Cut Line= 4
     1855779.742      260706.076     1855632.498      260828.364
     1855540.747      260885.474     1855429.373      261048.416
#Sta/Elev= 30
       0 1397.77    19.1  1391.9    47.8 1383.67   124.4 1364.81     134  1363.3
   191.4  1359.4   201.2 1357.71     211  1354.5   220.9 1350.71  228.02 1349.04
   230.7 1348.41   240.5 1348.64  242.921349.121   250.4 1350.59     270 1356.02
   279.8 1358.42  299.591362.599   308.9 1363.56   318.3 1363.93   327.7 1364.87
   337.1 1367.81  343.381370.589   346.5 1371.97   355.9 1375.16   365.3 1376.41
   384.1  1377.8   393.5 1378.84   402.9 1380.41   449.8 1389.64   496.8 1400.25
#Mann= 5 ,-1 , 0
       0     .12       0  228.02    .045       0  242.92     .12       0
  299.59    .016       0  343.38     .12       0
Bank Sta=228.02,242.92
XS Rating Curve= 0 ,0
Exp/Cntr=0.3,0.1

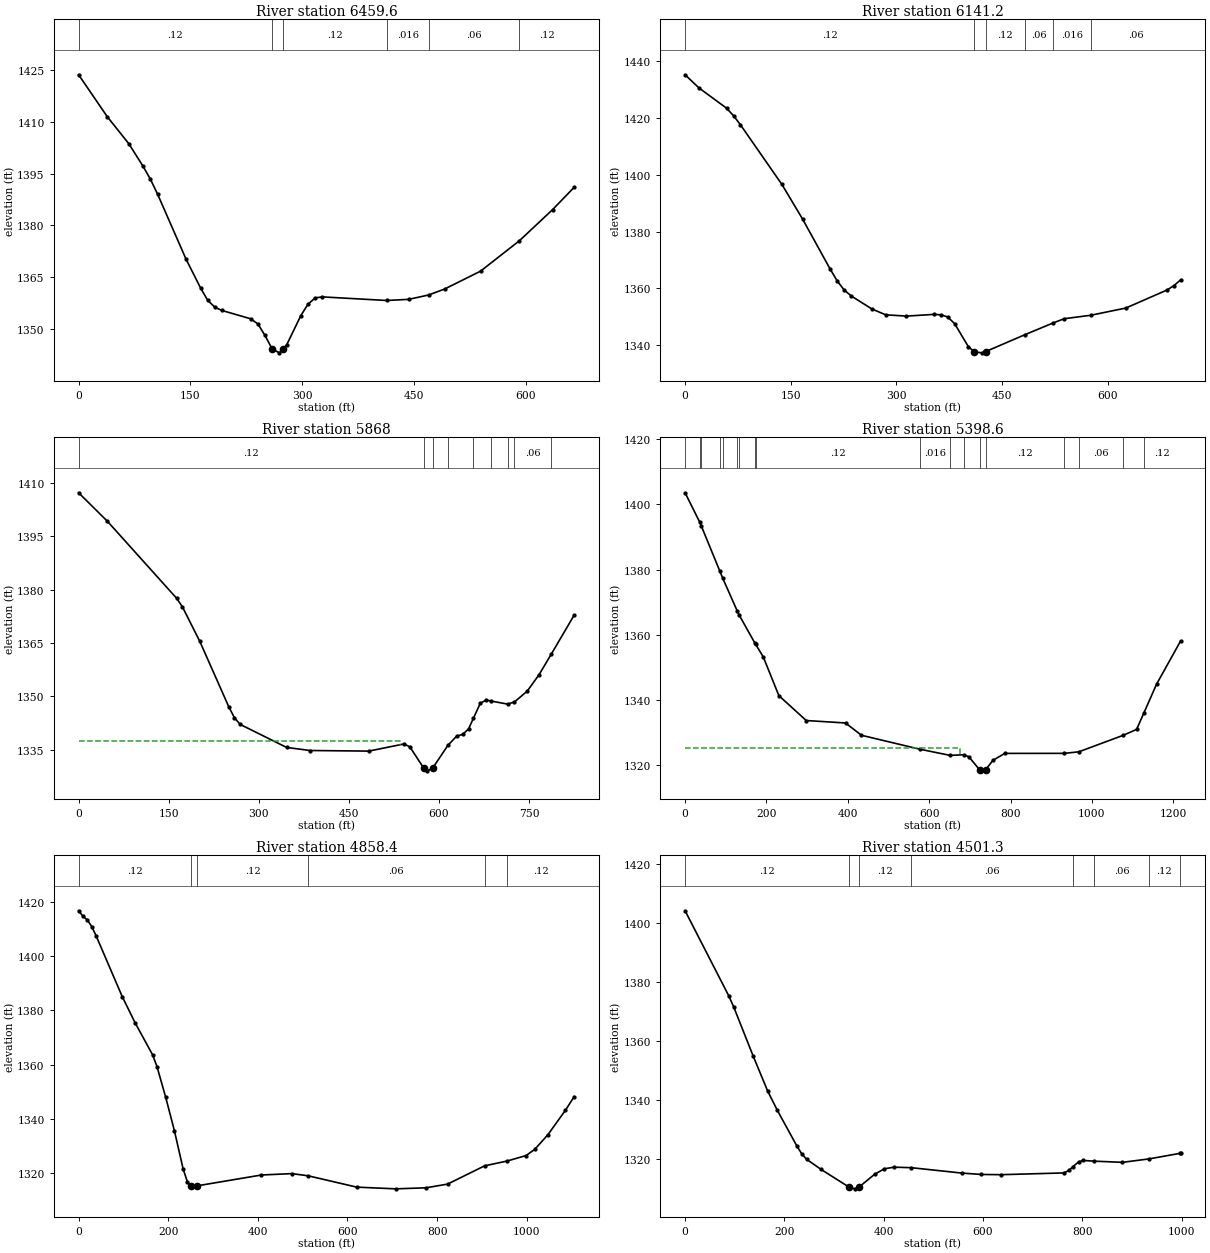
Type RM Length L Ch R = 1 ,6459.6  ,329.7,318.4,306.9
XS GIS Cut Line= 3
     1855634.425      260446.404      1855327.81      260694.249
     1855305.675       260963.78
#Sta/Elev= 30
       0 1423.69    38.5 1411.51    67.3 1403.71    86.5 1397.13    96.2 1393.45
   105.8 1389.13   144.2 1370.17   163.5 1361.91   173.1 1358.32   182.7 1356.29
   192.3 1355.35   230.8 1352.94   240.4 1351.46     250  1348.1   259.6 1344.19
   269.2 1343.07  274.331344.251   278.9 1345.31   298.1 1353.89   307.7 1357.17
   317.3    1359     327 1359.29  413.171358.251   442.6 1358.58  469.421359.838
   490.8 1361.56   539.1 1366.75  591.181375.563   635.7 1384.58   664.7 1391.07
#Mann= 6 ,-1 , 0
       0     .12       0   259.6    .045       0  274.33     .12       0
  413.17    .016       0  469.42     .06       0  591.18     .12       0
Bank Sta=259.6,274.33
XS Rating Curve= 0 ,0
Exp/Cntr=0.3,0.1

Type RM Length L Ch R = 1 ,6141.2  ,261.9,273.2,284.2
XS GIS Cut Line= 3
     1855516.612      260246.332     1855191.091      260384.353
     1855059.941       260708.95
#Sta/Elev= 30
       0 1435.25    19.6 1430.64    58.9 1423.47    68.8 1420.82    78.6 1417.63
   137.5 1396.61     167 1384.35   206.2  1366.7   216.1 1362.59   225.9 1359.43
   235.7 1357.37   265.2 1352.75   284.8 1350.69   314.3 1350.23   353.6 1350.84
   363.3 1350.68     373 1349.92   382.8 1347.55   402.2 1339.49  410.641337.635
   421.6 1337.29  426.671337.718   482.61343.688  522.331347.788   538.3 1349.31
  575.831350.519   625.9 1353.07   684.2 1359.41   693.9 1360.92   703.7 1362.98
#Mann= 6 ,-1 , 0
       0     .12       0  410.64    .045       0  426.67     .12       0
   482.6     .06       0  522.33    .016       0  575.83     .06       0
Bank Sta=410.64,426.67
XS Rating Curve= 0 ,0
Exp/Cntr=0.3,0.1

Type RM Length L Ch R = 1 ,5868    ,460.1,469.4,478.2
XS GIS Cut Line= 3
     1855425.466      260061.436     1855120.374      260178.142
     1854738.568      260498.596
#Sta/Elev= 30
       0 1407.21      48 1399.18   163.3 1377.51   172.9  1375.1   201.8  1365.4
   249.8  1347.1   259.4 1343.94     269 1342.06   346.2  1335.6   385.3 1334.73
     483 1334.56   541.7 1336.57   551.4 1335.77   574.4 1329.83   580.8 1329.01
   589.4 1329.75  614.96 1336.21   629.6  1338.8   639.4 1339.24   649.2 1340.79
  657.431343.822   668.7 1347.99   678.5 1348.93   685.91348.666  714.171347.781
  725.711348.391   746.9 1351.42   766.5 1356.02  787.161361.874   825.1 1372.81
#Mann= 9 ,-1 , 0
       0     .12       0   574.4    .045       0   589.4     .12       0
  614.96    .016       0  657.43     .12       0   685.9     .06       0
  714.17     .12       0  725.71     .06       0  787.16     .12       0
#XS Ineff= 2 , 0
          534.57  1337.4
Permanent Ineff=
       F       F
Bank Sta=574.4,589.4
XS Rating Curve= 0 ,0
Exp/Cntr=0.3,0.1

Type RM Length L Ch R = 1 ,5398.6  ,562.6,540.2,517
XS GIS Cut Line= 4
     1855416.352      260044.509     1855146.821      259798.416
     1854614.268      259965.082     1854482.758      260229.405
#Sta/Elev= 30
       0 1403.53   35.521394.626   40.23 1393.24   85.121379.582   92.741377.262
  128.15 1367.29  133.361365.928  171.171357.515  173.221357.099   192.1  1353.2
   230.5 1341.32   297.8 1333.68   394.4 1332.93   433.5 1329.16  577.131324.883
  651.251322.996  685.551323.185   697.8 1322.52  724.031318.567   727.2 1318.25
  738.781318.572   756.6 1321.45   785.9  1323.6  932.071323.612   967.71324.078
  1076.91329.146    1110 1330.96 1127.351335.859  1159.2 1344.88  1218.2 1358.08
#Mann= 18 ,-1 , 0
       0     .12       0   35.52     .06       0   40.23     .12       0
   85.12     .06       0   92.74     .12       0  128.15     .06       0
  133.36     .12       0  171.17     .06       0  173.22     .12       0
  577.13    .016       0  651.25     .06       0  685.55     .12       0
  724.03    .045       0  738.78     .12       0  932.07    .016       0
   967.7     .06       0  1076.9    .016       0 1127.35     .12       0
#XS Ineff= 2 , 0
          676.16 1325.14
Permanent Ineff=
       F       F
Bank Sta=724.03,738.78
XS Rating Curve= 0 ,0
Exp/Cntr=0.3,0.1

Type RM Length L Ch R = 1 ,4858.4  ,354.9,357.1,358.8
XS GIS Cut Line= 4
     1854727.116      259159.527     1854596.907      259617.426
     1854371.213      259953.798     1854347.341      260177.322
#Sta/Elev= 30
       0 1416.75     9.7 1414.73    19.4 1413.35    29.2 1410.93    38.9 1407.56
    97.2  1385.1   126.3 1375.31   165.2 1363.53   174.9 1359.21   194.3  1347.9
   213.7 1335.58   233.2 1321.45   242.9 1316.58  250.39  1315.3   252.6 1314.92
  265.271315.232     408 1319.21     476 1319.72   512.21318.912   620.7 1314.73
   707.5  1314.1     775 1314.48   823.3 1315.84  905.95 1322.59  955.57 1324.34
   998.4 1326.38    1018 1328.68  1047.3 1334.08  1086.4 1343.11  1105.9 1348.13
#Mann= 6 ,-1 , 0
       0     .12       0  250.39    .045       0  265.27     .12       0
   512.2     .06       0  905.95    .016       0  955.57     .12       0
Bank Sta=250.39,265.27
XS Rating Curve= 0 ,0
Exp/Cntr=0.3,0.1

Type RM Length L Ch R = 1 ,4501.3  ,444.4,436.1,425.9
XS GIS Cut Line= 2
     1854431.977      259120.464     1854078.244      260053.624
#Sta/Elev= 30
       0 1404.19      88 1375.31    97.8 1371.62     137 1354.94   166.3 1343.03
   185.9 1336.44     225 1324.42   234.8 1321.75   244.6 1319.89     274 1316.42
  330.791310.373   342.4 1309.85   349.7 1310.37   381.6 1314.78   401.1 1316.64
   420.7  1317.2  455.341317.031   557.7 1315.19   596.8 1314.73     636 1314.65
   763.1 1315.25   772.9 1316.08  780.92 1317.34   792.5    1319   802.3 1319.48
  824.061319.239   880.6 1318.84  933.391319.984  996.261321.877     998 1321.93
#Mann= 8 ,-1 , 0
       0     .12       0  330.79    .045       0   349.7     .12       0
  455.34     .06       0  780.92    .016       0  824.06     .06       0
  933.39     .12       0  996.26    .016       0
Bank Sta=330.79,349.7
XS Rating Curve= 0 ,0
Exp/Cntr=0.3,0.1

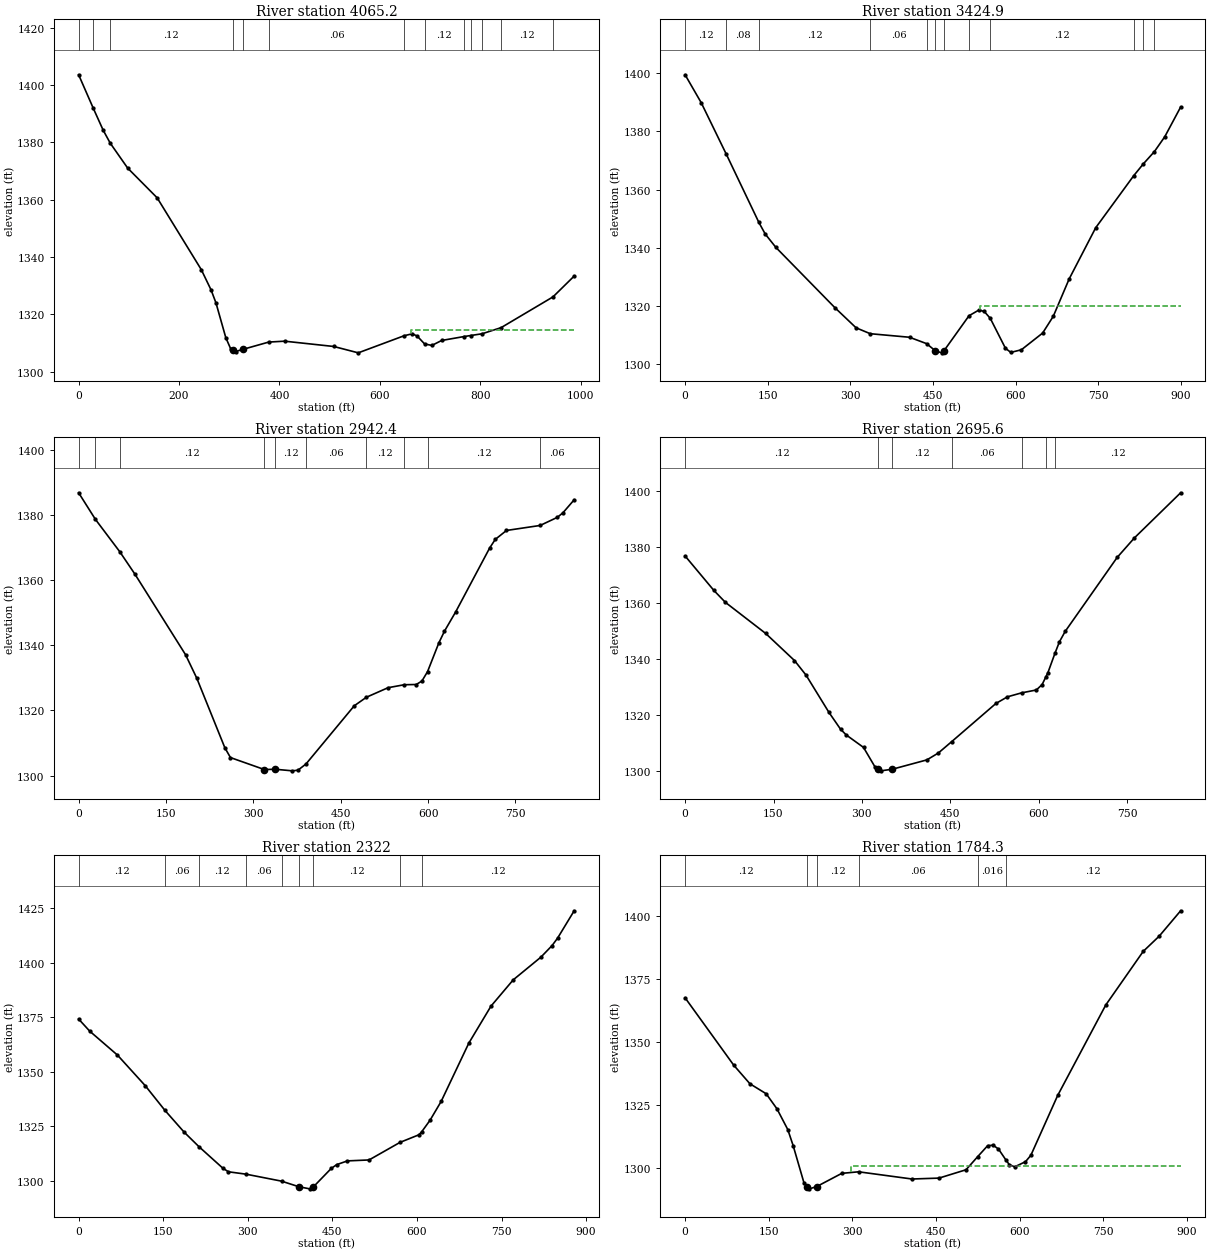
Type RM Length L Ch R = 1 ,4065.2  ,629.1,640.3,650
XS GIS Cut Line= 3
     1853904.633      259040.169     1853919.824      259450.325
     1853602.984      259932.096
#Sta/Elev= 30
       0  1403.6   29.01 1391.98    48.9 1384.25   63.031379.708    97.7 1371.02
   156.4 1360.65   244.3 1335.58   263.8  1328.5   273.6 1323.95   293.2  1311.8
   302.9 1307.94  306.561307.578   312.7 1306.98   326.5 1307.71  378.681310.288
   410.4  1310.6   508.2 1308.75     557 1306.53  648.421312.501   664.5 1313.18
   674.3  1312.4  689.161309.637   703.6 1309.12   723.2 1310.85  767.081312.198
  780.721312.572  803.521313.179  841.511315.321  944.911326.064   987.1 1333.33
#Mann= 13 ,-1 , 0
       0     .12       0   29.01     .08       0   63.03     .12       0
  306.56    .045       0   326.5     .12       0  378.68     .06       0
  648.42    .016       0  689.16     .12       0  767.08     .06       0
  780.72     .12       0  803.52     .06       0  841.51     .12       0
  944.91     .06       0
#XS Ineff= 2 , 0
                          661.51         1314.59
Permanent Ineff=
       F       F
Bank Sta=306.56,326.5
XS Rating Curve= 0 ,0
Exp/Cntr=0.3,0.1

Type RM Length L Ch R = 1 ,3424.9  ,474.1,482.4,490.4
XS GIS Cut Line= 3
     1853549.773      258945.822     1853343.357      259416.808
     1853101.682      259717.252
#Sta/Elev= 30
       0 1399.45    29.1 1389.92   74.871372.155  134.021348.739   145.5 1344.77
   164.9 1340.17   271.7 1319.54   310.5 1312.57  336.211310.548   407.5 1309.33
  438.411307.146  454.121304.725   465.7 1303.98  469.35  1304.5  515.56 1316.72
   533.5 1318.68   543.2 1318.18  554.091315.841   581.7 1305.55   591.4 1304.13
   610.6 1305.03   649.2 1310.77   668.5 1316.51   697.4 1329.36   745.6 1346.94
  814.81 1364.85  832.191368.886  852.121373.069   870.9 1378.15   899.8 1388.37
#Mann= 12 ,-1 , 0
       0     .12       0   74.87     .08       0  134.02     .12       0
  336.21     .06       0  438.41     .12       0  454.12    .045       0
  469.35     .12       0  515.56    .016       0  554.09     .12       0
  814.81     .06       0  832.19     .12       0  852.12     .06       0
#XS Ineff= 2 , 0
                           535.6          1320.1
Permanent Ineff=
       F       F
Bank Sta=454.12,469.35
XS Rating Curve= 0 ,0
Exp/Cntr=0.3,0.1

Type RM Length L Ch R = 1 ,2942.4  ,262,246.8,231.5
XS GIS Cut Line= 3
     1853318.696      258794.943     1852997.515      259129.145
     1852817.393      259472.027
#Sta/Elev= 30
       0 1386.83   28.911378.644   70.461368.773    96.6 1361.86   183.5 1337.13
   202.8 1329.92   251.1 1308.51   260.7 1305.52   318.7 1301.86     338 1301.93
     367 1301.45   376.6 1301.65  390.33 1303.55   473.2 1321.42  494.171324.056
   531.3 1326.98  559.171327.889   579.7 1327.96   589.4 1329.03  599.051331.905
   618.4 1340.71   628.1 1344.33   647.5  1350.3   705.6 1369.84   715.3 1372.51
   734.6 1375.26  792.371376.796   821.8 1379.28   831.5 1380.68   850.8 1384.68
#Mann= 10 ,-1 , 0
       0     .12       0   28.91     .08       0   70.46     .12       0
   318.7    .045       0     338     .12       0  390.33     .06       0
  494.17     .12       0  559.17    .016       0  599.05     .12       0
  792.37     .06       0
Bank Sta=318.7,338
XS Rating Curve= 0 ,0
Exp/Cntr=0.3,0.1

Type RM Length L Ch R = 1 ,2695.6  ,352.2,373.6,394.9
XS GIS Cut Line= 3
      1852915.05       258590.95     1852867.307      259116.124
     1852706.716      259385.221
#Sta/Elev= 30
       0 1376.92    48.8  1364.6    68.4 1360.32   136.7  1349.2   185.6  1339.5
   205.1 1334.31   244.1 1320.93   263.7 1314.94   273.4 1312.87   302.7 1308.41
   322.3 1301.38  327.951300.597     332 1300.03   351.6 1300.61   410.2 1303.95
   429.7 1306.42  452.421310.505   527.3 1324.14   546.9 1326.52  570.721327.928
   595.9 1328.97   605.7  1330.9  612.081333.667   615.5 1335.15  627.491342.104
   635.1 1346.22   644.8 1349.92     733  1376.4   762.4 1383.42   840.7 1399.54
#Mann= 7 ,-1 , 0
       0     .12       0  327.95    .045       0   351.6     .12       0
  452.42     .06       0  570.72    .016       0  612.08     .06       0
  627.49     .12       0
Bank Sta=327.95,351.6
XS Rating Curve= 0 ,0
Exp/Cntr=0.3,0.1

Type RM Length L Ch R = 1 ,2322    ,554.2,537.7,521.2
XS GIS Cut Line= 4
      1852767.48      258510.655     1852637.272      258764.561
     1852439.789      258881.749     1852355.154      259235.482
#Sta/Elev= 30
       0 1374.13    19.7 1368.57    68.9 1357.59   118.1 1343.57  152.951332.269
     187 1322.28  213.071315.661   255.8  1305.7   265.7 1304.07  296.681302.983
  359.761299.782   390.6 1297.21   409.7 1296.25   415.6 1296.98     448 1305.62
   457.6 1307.36   476.7 1309.07     515  1309.5  569.761317.543   603.4 1321.04
   608.21322.373   623.1  1327.7   642.8 1336.33   691.9 1363.09   731.2 1380.05
   770.6  1392.1   819.7 1402.52   839.4  1407.8   849.2 1411.21   878.7 1423.79
#Mann= 9 ,-1 , 0
       0     .12       0  152.95     .06       0  213.07     .12       0
  296.68     .06       0  359.76     .12       0   390.6    .045       0
   415.6     .12       0  569.76    .016       0   608.2     .12       0
Bank Sta=390.6,415.6
XS Rating Curve= 0 ,0
Exp/Cntr=0.3,0.1

Type RM Length L Ch R = 1 ,1784.3  ,283.7,288.3,292.7
XS GIS Cut Line= 3
      1852294.39      258282.791     1852099.077      258881.749
     1852079.546      259139.995
#Sta/Elev= 30
       0 1367.59    87.2 1340.81   116.3  1333.4   145.4 1329.44   164.8 1323.44
   184.2  1315.2   193.8 1308.84   213.2 1294.04  219.571292.446   222.9 1291.61
  236.031292.504   281.1 1297.77  311.261298.387   407.1 1295.52   455.5 1295.88
     504  1299.2  525.121304.467   542.8 1308.78   552.5 1308.97   562.2 1307.45
  575.281303.175   581.5 1301.27   591.2 1300.36   610.6 1302.39   620.3 1304.95
   668.4 1328.75   754.7 1364.74   821.8 1386.04   850.6 1392.13     889 1402.21
#Mann= 6 ,-1 , 0
       0     .12       0  219.57    .045       0  236.03     .12       0
  311.26     .06       0  525.12    .016       0  575.28     .12       0
#XS Ineff= 2 , 0
                          297.75         1300.51
Permanent Ineff=
       F       F
Bank Sta=219.57,236.03
XS Rating Curve= 0 ,0
Exp/Cntr=0.3,0.1

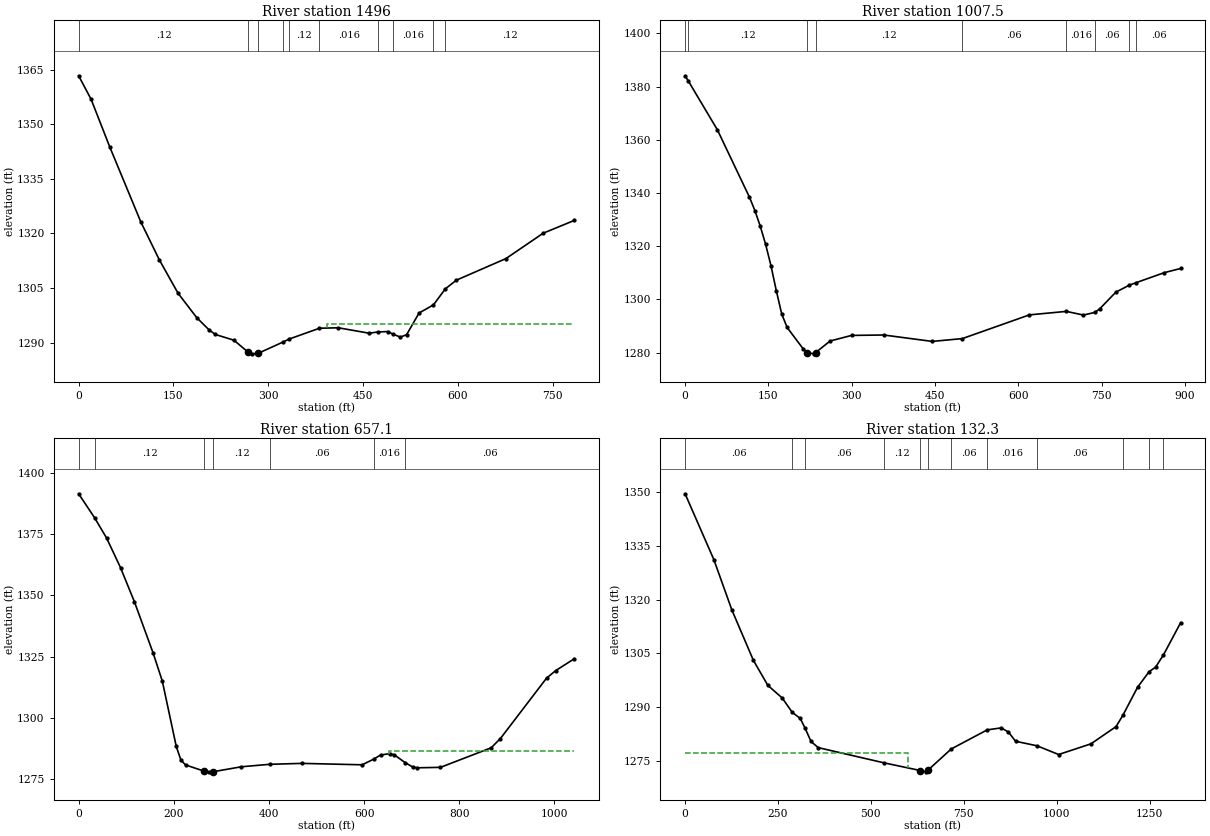
Type RM Length L Ch R = 1 ,1496    ,487.1,488.5,489.4
XS GIS Cut Line= 4
     1852127.289      258209.006      1851977.55      258365.256
     1851886.404      258525.846     1851634.668      258814.475
#Sta/Elev= 30
       0 1363.33    19.7 1356.88    49.2 1343.79    98.4 1323.15   127.9 1312.66
   157.4 1303.53   186.9 1296.84   206.6 1293.45   216.4 1292.22   245.6 1290.65
   268.4 1287.33   274.7  1286.9   284.4 1287.07  323.621290.158  332.691290.943
  381.06 1293.94   410.9 1294.06     460 1292.56  473.211292.921   489.4 1293.02
  497.171292.322   509.1  1291.5   518.9 1292.17   538.6 1298.12  561.411300.369
  580.121304.753   597.5 1307.14     676 1313.08     735 1320.06     784 1323.56
#Mann= 10 ,-1 , 0
       0     .12       0   268.4    .045       0   284.4     .12       0
  323.62     .06       0  332.69     .12       0  381.06    .016       0
  473.21     .12       0  497.17    .016       0  561.41     .06       0
  580.12     .12       0
#XS Ineff= 2 , 0
                          392.16         1295.03
Permanent Ineff=
       F       F
Bank Sta=268.4,284.4
XS Rating Curve= 0 ,0
Exp/Cntr=0.3,0.1

Type RM Length L Ch R = 1 ,1007.5  ,349.2,350.4,351.7
XS GIS Cut Line= 3
     1851788.748      257853.103     1851571.734      258195.985
     1851569.564      258682.096
#Sta/Elev= 30
       0 1384.05    5.761382.102      58 1363.79   115.9 1338.41   125.6 1333.42
   135.3 1327.52   144.9 1320.75   154.6 1312.65   164.2 1303.28   173.9 1294.56
   183.6  1289.5   212.6 1281.43  219.951280.074   231.9 1279.58  234.931280.046
   260.9 1284.39   299.5  1286.5   357.5 1286.66   444.7 1284.25   498.91285.302
   619.7 1294.22   686.31295.531   716.9 1294.15  737.541295.154   746.1 1296.46
   775.2 1302.74  799.36 1305.37  812.041306.343   862.7  1310.1   891.9 1311.65
#Mann= 9 ,-1 , 0
       0     .06       0    5.76     .12       0  219.95    .045       0
  234.93     .12       0   498.9     .06       0   686.3    .016       0
  737.54     .06       0  799.36     .12       0  812.04     .06       0
Bank Sta=219.95,234.93
XS Rating Curve= 0 ,0
Exp/Cntr=0.3,0.1

Type RM Length L Ch R = 1 ,657.1   ,558.7,524.7,489.7
XS GIS Cut Line= 3
     1851528.331      257638.259      1851204.98      258091.818
     1851122.515      258569.249
#Sta/Elev= 30
       0 1391.48   33.36 1381.75    58.6 1373.49      88 1361.38   117.3  1347.4
   156.4 1326.62   175.9 1315.08   205.2 1288.44     215 1282.86   224.8 1280.89
   264.3 1278.32   273.6 1278.08   283.4 1278.15     342 1280.15   401.6 1281.15
   469.1 1281.53   595.8 1280.95  619.921283.229   634.5 1284.93   653.9  1285.5
   663.6    1285     6861281.875   702.4 1280.02   712.1 1279.73   760.5 1279.91
   867.1 1287.89   886.5 1291.67   983.4 1316.28  1002.8 1319.38  1041.5 1324.17
#Mann= 7 ,-1 , 0
       0     .06       0   33.36     .12       0   264.3    .045       0
   283.4     .12       0   401.6     .06       0  619.92    .016       0
     686     .06       0
#XS Ineff= 2 , 0
                          651.39         1286.72
Permanent Ineff=
       F       F
Bank Sta=264.3,283.4
XS Rating Curve= 0 ,0
Exp/Cntr=0.3,0.1

Type RM Length L Ch R = 1 ,132.3   ,144.8,132.3,120.5
XS GIS Cut Line= 4
     1851157.237       257490.69     1850783.973       257798.85
     1851063.921      258020.204     1850972.775      258504.145
#Sta/Elev= 30
       0 1349.45    77.4 1331.12   125.8 1317.13   183.9 1303.06   222.7 1296.12
   261.4 1292.61   288.31288.606   309.8 1286.93  322.421284.317   338.8 1280.52
   358.2  1278.8  534.141274.591   633.41272.413     648 1272.06   653.2 1272.49
  716.15 1278.43  813.071283.746   850.6 1284.29   869.9 1283.15   889.2 1280.57
  946.861279.311  1005.1 1276.88    1092 1279.85  1159.6 1284.65 1177.821287.764
  1217.5  1295.6 1248.651299.952  1265.8 1301.16 1287.06 1304.59  1333.4 1313.56
#Mann= 12 ,-1 , 0
       0     .06       0   288.3    .016       0  322.42     .06       0
  534.14     .12       0   633.4    .045       0   653.2     .12       0
  716.15     .06       0  813.07    .016       0  946.86     .06       0
 1177.82     .12       0 1248.65     .06       0 1287.06     .12       0
#XS Ineff= 2 , 0
          599.59 1277.23
Permanent Ineff=
       F       F
Bank Sta=633.4,653.2
XS Rating Curve= 0 ,0
Exp/Cntr=0.3,0.1
LCMann Table=0

Chan Stop Cuts=-1
Use User Specified Reach Order=0
Composite Channel Slope=5